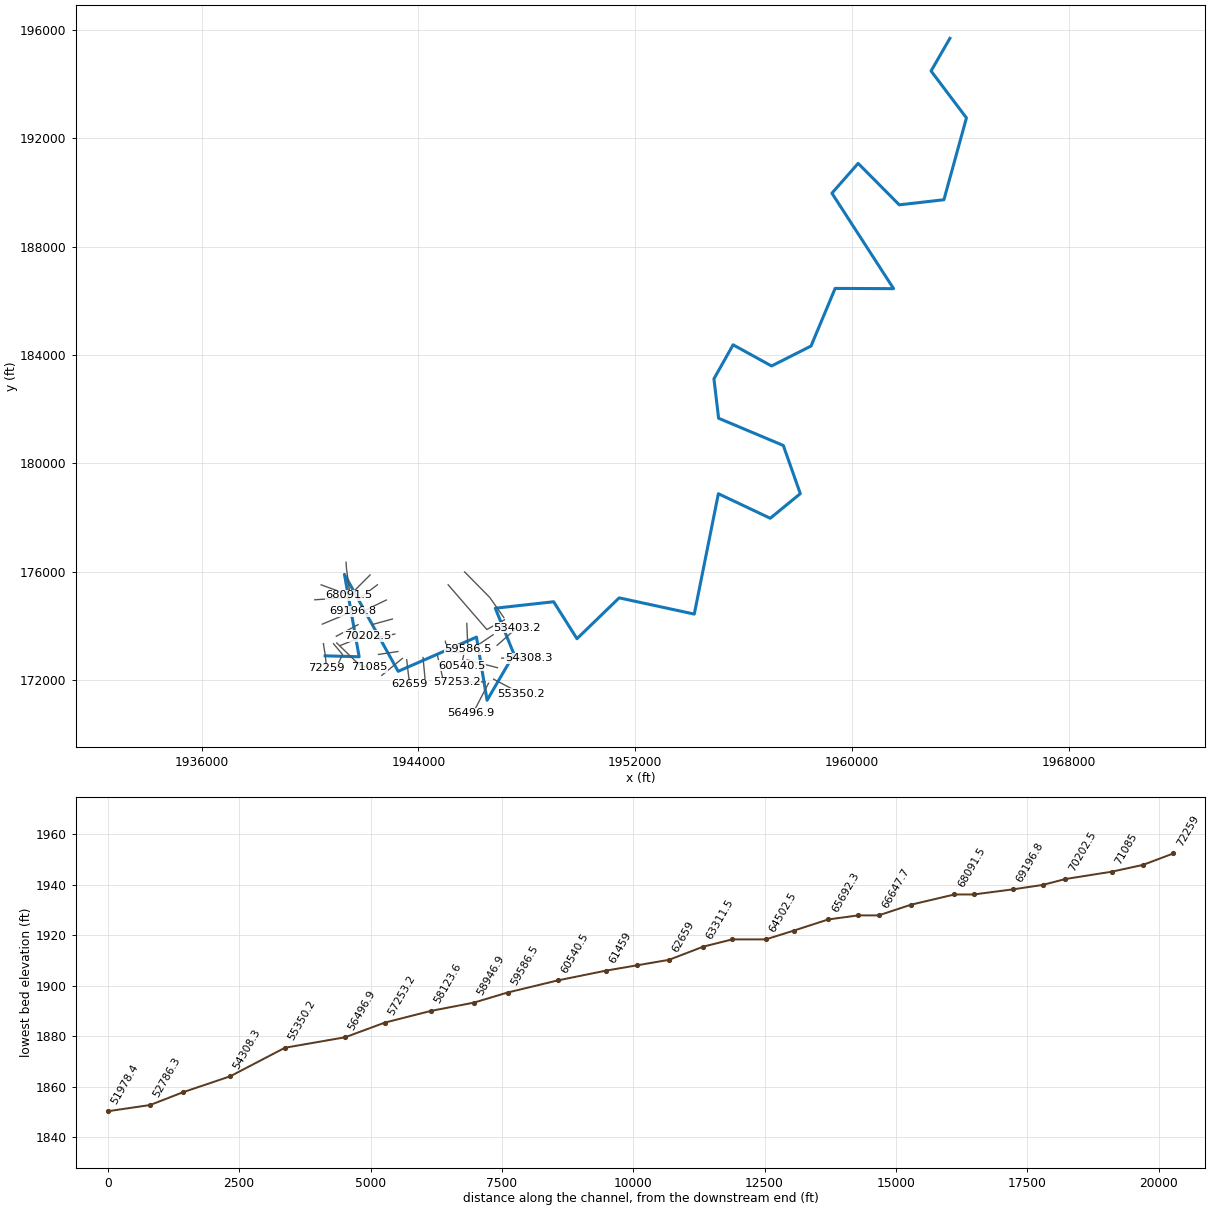
--- BlstnRvr.prj (project) ---

Proj Title=BlstnRvr
Current Plan=p01
Default Exp/Contr=0,0
English Units
Geom File=g01
Flow File=f01
Plan File=p01
BEGIN DESCRIPTION:
END DESCRIPTION:
DSS Export Rating Curves= 0
DSS Export Rating Curve Sorted= 0
DSS Export Volume Flow Curves= 0
DXF OffsetX= 0
DXF OffsetY= 0
DXF ScaleX= 0
DXF ScaleY= 0

--- BlstnRvr.p01 (plan) ---

Plan Title=Floodplain
Program Version=4.00
Geom File=g01
Flow File=f01
K Sum by GR=0
Std Step Tol=0.01
Critical Tol=0.01
Num of Std Step Trials=20
Max Error Tol=0.3
Flow Tol Ratio=0.001
Split Flow NTrial=30
Split Flow Tol=0.02
Split Flow Ratio=0.02
Log Output Level=0
Friction Slope Method=1
Unsteady Friction Slope Method=2
Unsteady Bridges Friction Slope Method=1
Global Log Level=0
CheckData=False
Run HTab=0
Run UNet=0
Run PostProcess=0
UNET Theta=0
UNET Theta Warmup=0
UNET ZTol=0
UNET ZSATol=0
UNET MxIter=0
UNET MaxInSteps=0
UNET DtIC=0
UNET DtMin=0
UNET MaxCRTS=0
UNET WFStab=0
UNET SFStab=0
UNET WFX=0
UNET SFX=0
UNET DSS MLevel=0
UNET DZMax Abort=0
UNET Convert EG Bridges=0
UNET Use Existing IB Tables=0
UNET Froude Limit=0
UNET Froude Power=0
Write IC File=0
Echo Input=False
Echo Output=False
Write Detailed=0

--- BlstnRvr.f01 (steady flow) ---

Flow Title=NFF Regression Equation
Program Version=4.00
Number of Profiles=1
Profile Names=P100yr
River Rch & RM=BlstnRvr,Main      ,72259
26618.37
River Rch & RM=BlstnRvr,Main      ,46335.9
26669.32
River Rch & RM=BlstnRvr,Main      ,45859
32226.22
River Rch & RM=BlstnRvr,Main      ,237.6
35409.37
Boundary for River Rch & Prof#=BlstnRvr,Main      ,1
Up Type=0
Dn Type=3
Dn Slope=0.005718

--- BlstnRvr.g01 (geometry) ---

Geom Title=USGS 3m DEM
Program Version=4.10

River Reach=BlstnRvr        ,Main
Reach XY= 30
     1940561.005      172887.943     1941816.687       172853.32
     1941274.936      175894.636     1943256.213      172315.495
     1946146.464      173578.664     1946537.089      171247.067
     1947530.315      172949.462     1946840.177      174645.783
     1948993.687      174884.219     1949854.797      173519.636
     1951412.089      175028.317     1954183.084      174428.876
     1955072.803      178873.266     1956987.163       177966.79
     1958096.652      178875.689     1957468.778      180654.587
     1955081.273      181659.648     1954908.966      183114.939
     1955616.264      184370.762     1957035.353      183589.081
     1958491.475      184325.406     1959380.917      186452.814
     1961538.368      186444.765     1959262.783      189969.289
      1960230.05      191069.931     1961748.511      189538.614
     1963395.381       189727.33     1964226.325      192748.803
      1962921.19      194480.538      1963615.73      195686.619

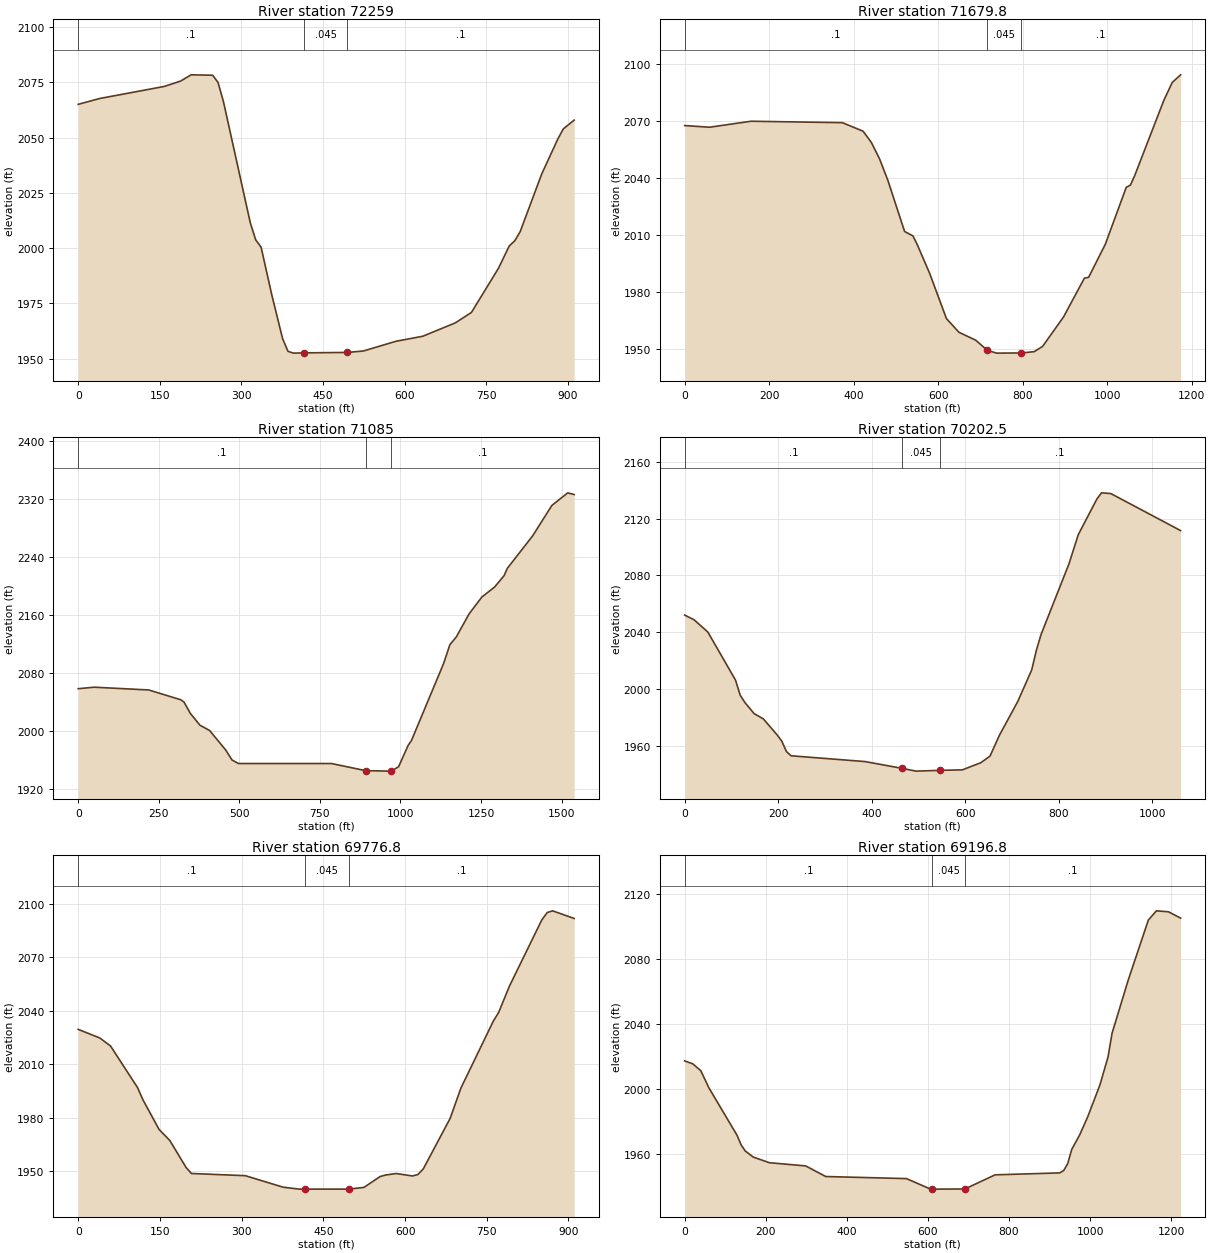
Type RM Length L Ch R = 1 ,72259   ,612.8,579.2,549.8
XS GIS Cut Line= 3
     1940497.588      173338.321     1940570.874      172889.555
     1940609.643      172434.567
#Sta/Elev= 30
       0 2065.04    39.5 2067.68   158.2 2073.14   187.8 2075.53   207.6 2078.39
   247.1 2078.21     257 2074.92   266.9 2066.27   316.3 2011.39   326.2 2003.74
   336.1  2000.4   355.9 1978.68   375.6 1959.04   385.5 1953.31   395.4 1952.48
   414.7 1952.59   494.7  1952.8   524.2 1953.45   583.8 1957.83   633.4 1960.13
     693 1966.16   722.7  1970.9   772.4  1990.9   792.2    2001   802.2 2003.27
   812.1 2007.37   851.8 2033.53   881.6 2049.46   891.5 2053.93   911.4  2057.9
#Mann= 3 , 0 , 0
       0      .1       0   414.7    .045       0   494.7      .1       0
Bank Sta=414.7,494.7
XS Rating Curve= 0 ,0
Exp/Cntr=0.3,0.1

Type RM Length L Ch R = 1 ,71679.8 ,525.2,594.8,664.4
XS GIS Cut Line= 3
     1940871.549      173334.333     1941204.388      172934.153
     1940923.333      172344.447
#Sta/Elev= 30
       0 2067.44    58.9 2066.57   157.1 2069.72   373.2 2068.96   422.3 2064.48
   441.9 2058.57   461.6 2049.78   481.2 2038.48   520.5 2011.82   540.3 2009.48
   550.2 2005.07   579.9 1989.78   619.5 1966.08   649.2 1958.86   688.8 1954.72
   716.4 1949.38   738.3 1947.92   796.4    1948   827.3 1948.69   847.1 1951.45
   896.6 1966.89   946.1 1987.31     956 1987.72   995.6 2005.11  1045.1 2034.99
    1055 2036.19  1064.9 2041.02  1134.2 2080.74    1154 2090.09  1173.8 2094.09
#Mann= 3 , 0 , 0
       0      .1       0   716.4    .045       0   796.4      .1       0
Bank Sta=716.4,796.4
XS Rating Curve= 0 ,0
Exp/Cntr=0.3,0.1

Type RM Length L Ch R = 1 ,71085   ,817,882.5,948
XS GIS Cut Line= 3
     1940990.981      173361.879     1941862.448      172517.758
     1942184.353      172466.646
#Sta/Elev= 30
       0 2058.82    49.7  2060.9   218.8 2057.09   318.2  2043.6   328.2 2040.47
   348.1 2024.75   377.9 2008.48   407.7  2001.3   457.5 1974.52   477.4 1960.58
   497.2 1955.72   785.6 1955.75   892.2 1945.88   964.6 1945.23   972.2 1945.28
   994.5 1951.43  1024.3    1981  1034.2 1987.34  1133.7 2093.16  1153.6 2119.54
  1173.5 2130.21  1213.3 2162.06  1252.8 2185.18  1292.3 2198.92  1321.9 2214.75
  1331.8 2224.69  1410.8 2269.73  1470.1 2311.43  1519.4 2328.78  1539.2 2326.39
#Mann= 3 , 0 , 0
       0      .1       0   892.2    .045       0   972.2      .1       0
Bank Sta=892.2,972.2
XS Rating Curve= 0 ,0
Exp/Cntr=0.3,0.1

Type RM Length L Ch R = 1 ,70202.5 ,419.9,425.7,431.5
XS GIS Cut Line= 3
     1941127.969      173271.297     1941806.752      173545.507
     1942125.915      173621.926
#Sta/Elev= 30
       0 2052.13    19.8 2048.91    49.5 2040.23   108.8 2006.32   118.7 1995.75
   128.6 1990.67   148.4 1982.83   168.2 1979.08   197.9 1967.73   207.8 1963.31
   217.6 1956.09   227.5 1953.12   385.8 1949.04   465.6 1944.23   494.6 1942.32
   545.6 1942.86   593.6 1943.21   633.2 1948.25   652.9 1952.93   672.7 1967.42
   712.3 1991.44     742 2013.62     752 2027.49   761.9 2038.45   821.6 2088.18
   841.5 2108.74   881.2 2133.76   891.2 2138.18   911.1 2137.67  1060.3 2111.59
#Mann= 3 , 0 , 0
       0      .1       0   465.6    .045       0   545.6      .1       0
Bank Sta=465.6,545.6
XS Rating Curve= 0 ,0
Exp/Cntr=0.3,0.1

Type RM Length L Ch R = 1 ,69776.8 ,585.1,580,574.9
XS GIS Cut Line= 2
     1940973.591      173611.294     1941777.971      174037.772
#Sta/Elev= 30
       0 2029.56    39.6 2024.74    59.4 2020.21   108.9 1996.94   118.8 1990.09
   148.4 1973.48   168.2 1967.25   197.9  1952.2   207.8 1948.77   306.8 1947.53
     376  1941.1   405.7    1940   416.3    1940   496.3    1940   524.5 1940.96
   554.2 1947.05   564.1 1947.91   583.9 1948.74   613.6 1947.38   623.5 1948.18
   633.4 1951.31   682.8 1979.68   702.6 1996.69     762 2034.17   771.9  2039.1
   791.7 2053.86   851.1 2090.95     861 2095.07   870.9 2096.01   910.4 2091.73
#Mann= 3 , 0 , 0
       0      .1       0   416.3    .045       0   496.3      .1       0
Bank Sta=416.3,496.3
XS Rating Curve= 0 ,0
Exp/Cntr=0.3,0.1

Type RM Length L Ch R = 1 ,69196.8 ,758.7,740.5,722.3
XS GIS Cut Line= 2
     1940458.176      174057.966     1941586.485      174529.968
#Sta/Elev= 30
       0 2017.13    19.9 2015.35    39.8  2011.1    59.7 2000.57   129.3 1971.29
   139.2 1965.46   149.2 1961.74     169 1957.95   208.8 1954.46   298.3 1952.49
     348 1945.96   546.9 1944.68   606.6  1938.2   611.1  1938.2   691.1 1938.29
   765.6    1947   924.8 1948.19   934.7 1949.63   944.6 1953.88   954.6 1962.65
   974.5 1971.74   994.4 1982.98  1024.2 2002.42  1044.1 2019.57    1054 2034.14
  1093.8 2066.82  1143.5 2103.82  1163.4 2109.52  1193.2 2108.92  1223.1 2105.05
#Mann= 3 , 0 , 0
       0      .1       0   611.1    .045       0   691.1      .1       0
Bank Sta=611.1,691.1
XS Rating Curve= 0 ,0
Exp/Cntr=0.3,0.1

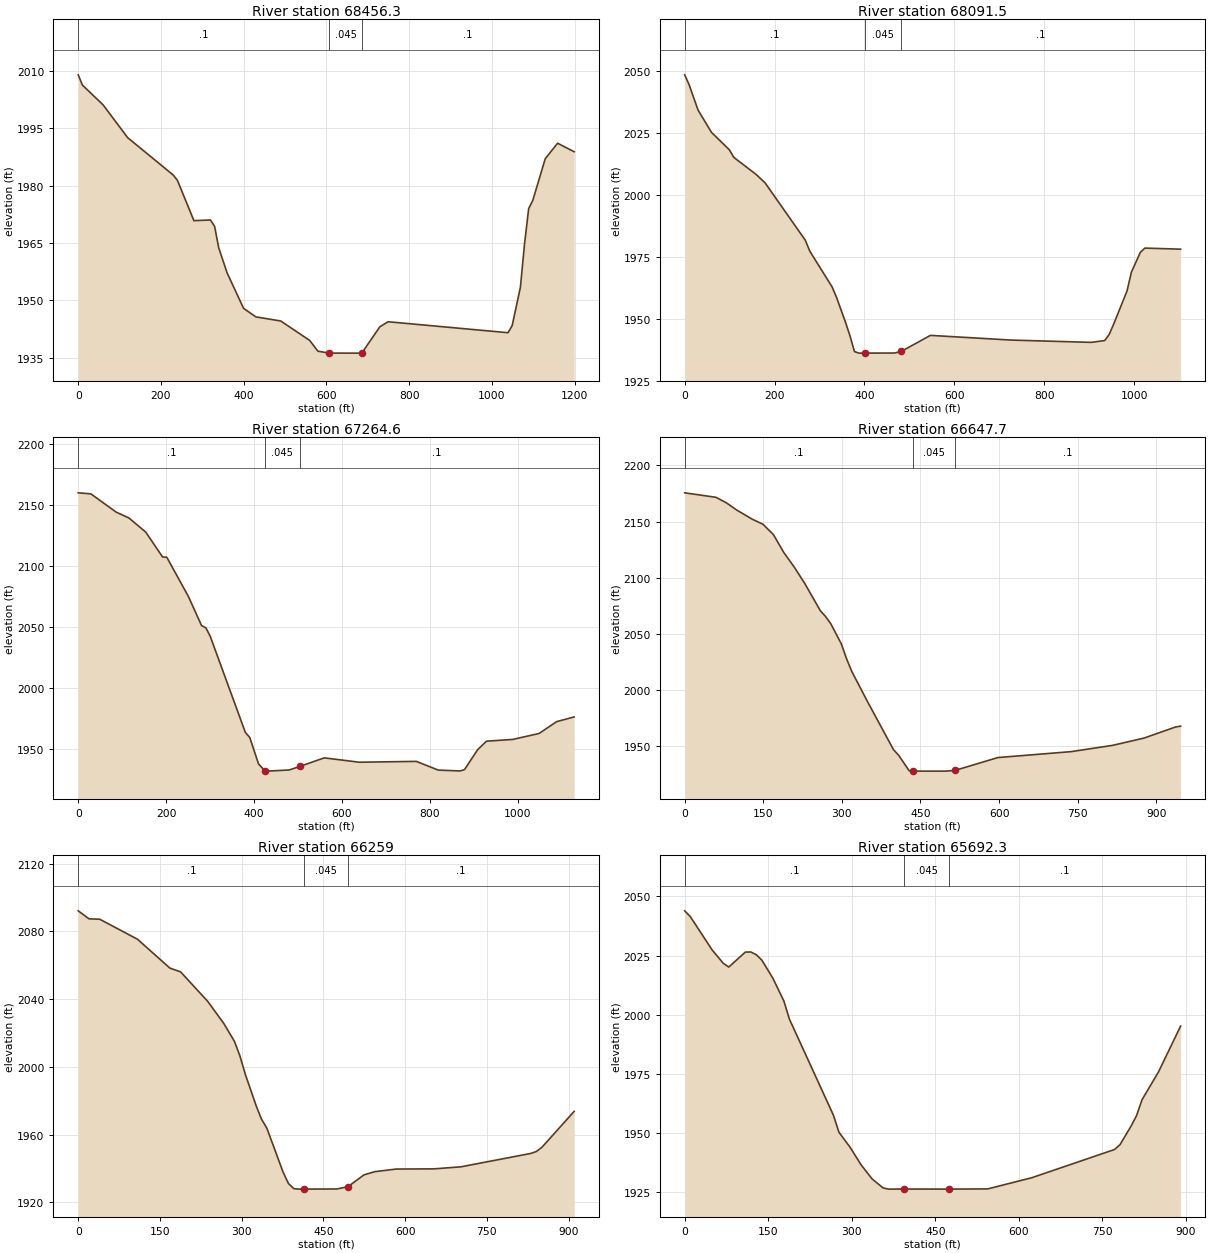
Type RM Length L Ch R = 1 ,68456.3 ,388.4,364.8,341.3
XS GIS Cut Line= 2
      1940179.47      174957.017     1941375.208      175037.931
#Sta/Elev= 30
       0    2009      10 2006.33    59.9 2001.17   119.8 1992.53   229.7 1982.78
   239.7 1981.41   279.6 1970.85   319.6 1971.02   329.6 1969.36   339.6 1963.73
   359.5 1957.27   399.5 1947.92   429.4 1945.67   489.4  1944.6   559.3 1939.52
   579.3  1936.7   606.2  1936.2   679.1 1936.19   686.2 1936.33   729.1 1943.11
     749  1944.4  1038.7 1941.53  1048.7 1943.38  1068.6 1953.42  1078.6 1964.75
  1088.6    1974  1098.6 1976.16  1128.6 1987.04  1158.5 1991.11  1198.5 1988.88
#Mann= 3 , 0 , 0
       0      .1       0   606.2    .045       0   686.2      .1       0
Bank Sta=606.2,686.2
XS Rating Curve= 0 ,0
Exp/Cntr=0.3,0.1

Type RM Length L Ch R = 1 ,68091.5 ,886.8,826.9,767
XS GIS Cut Line= 2
     1940415.824      175508.993     1941451.627      175127.836
#Sta/Elev= 30
       0 2048.45     9.9 2044.46    29.8 2034.22    59.7 2025.23    99.4 2018.21
   109.4 2015.14   159.1 2008.26     179 2004.86   268.5 1981.72   278.4 1977.34
   328.1 1962.89   338.1 1958.62     358 1948.57   367.9 1943.17   377.8 1936.82
   387.8 1936.19     402  1936.2   467.3 1936.23     482 1936.88   546.9 1943.35
   725.9 1941.46   904.8 1940.53   934.7 1941.26   944.6 1943.67   954.6 1947.84
   984.4 1961.26   994.3 1968.91  1014.2 1976.88  1024.2 1978.56  1103.7 1978.12
#Mann= 3 , 0 , 0
       0      .1       0     402    .045       0     482      .1       0
Bank Sta=402,482
XS Rating Curve= 0 ,0
Exp/Cntr=0.3,0.1

Type RM Length L Ch R = 1 ,67264.6 ,668.2,616.8,565.5
XS GIS Cut Line= 3
     1941334.751      176341.555     1941348.236      176121.287
     1941469.608      175222.237
#Sta/Elev= 30
       0 2160.13    28.8 2159.29    86.4 2144.31   115.1 2139.59   153.5    2128
   191.9 2107.57   201.5 2107.34   250.6 2075.23   280.5 2051.41   290.5 2049.45
   300.4 2042.45   380.2 1963.78   390.2 1959.66   410.1 1938.05   424.3 1932.52
     430 1932.13   479.9 1933.07   504.3 1936.03   559.6    1943   639.4 1939.42
     769 1940.11   818.8 1932.99   868.7 1932.27   878.6 1933.38   908.6 1949.78
   928.5 1956.66   988.3  1958.1  1048.1 1962.97    1088 1972.65  1127.9 1976.54
#Mann= 3 , 0 , 0
       0      .1       0   424.3    .045       0   504.3      .1       0
Bank Sta=424.3,504.3
XS Rating Curve= 0 ,0
Exp/Cntr=0.3,0.1

Type RM Length L Ch R = 1 ,66647.7 ,396.2,388.8,381.3
XS GIS Cut Line= 2
     1942220.315      175874.048     1941552.923      175202.839
#Sta/Elev= 30
       0 2175.53    59.8 2171.54    79.7 2166.59    99.6 2160.12   129.5 2151.94
   149.4  2147.6   169.4 2138.35   189.3 2122.34   209.2 2109.42   229.2 2094.88
     259 2070.58     269 2065.45     279 2058.92   298.9 2041.21   308.9 2027.97
   318.8 2016.71   348.7 1989.94   398.5 1947.04   408.5 1941.95   428.4 1928.25
   435.8    1928   448.4  1927.9   498.2  1927.9   515.8 1928.53   597.8 1939.97
   737.3 1945.23     817 1950.85   876.8 1957.33   936.6 1967.13   946.5 1967.94
#Mann= 3 , 0 , 0
       0      .1       0   435.8    .045       0   515.8      .1       0
Bank Sta=435.8,515.8
XS Rating Curve= 0 ,0
Exp/Cntr=0.3,0.1

Type RM Length L Ch R = 1 ,66259   ,577.8,566.6,555.4
XS GIS Cut Line= 3
     1942490.804       175511.49     1942129.329      175235.155
     1941767.854       174958.82
#Sta/Elev= 30
       0  2092.1    19.8 2087.38    39.6 2087.13   108.8 2075.34   168.2  2058.3
   187.9 2056.08   237.4 2038.78   267.1 2025.66   286.8 2015.01   296.7  2006.5
   306.6 1995.65   326.4 1977.19   336.3 1969.19   346.2 1963.81   375.9 1937.95
   385.8 1931.18   395.6 1928.18   405.5 1927.89     415  1927.9   474.8 1927.99
     495 1929.33   524.2 1936.28     544 1938.18   583.6 1939.74   652.8 1939.85
   702.3 1941.05   830.9 1948.98   840.8 1950.11   850.6 1952.49     910 1973.77
#Mann= 3 , 0 , 0
       0      .1       0     415    .045       0     495      .1       0
Bank Sta=415,495
XS Rating Curve= 0 ,0
Exp/Cntr=0.3,0.1

Type RM Length L Ch R = 1 ,65692.3 ,669.1,659,648.9
XS GIS Cut Line= 2
     1942818.184      174948.026     1942016.649      174560.125
#Sta/Elev= 30
       0 2043.89     9.9 2041.52    49.5  2027.3    69.3 2021.73    79.2 2020.13
   108.8 2026.44   118.7 2026.51   128.6 2025.34   138.5 2023.08   158.3 2015.44
   178.1 2005.81     188 1998.16   267.1 1957.53     277 1950.33   296.8 1944.07
   316.6 1936.62   336.4 1930.64   356.2 1926.82   366.1  1926.3   394.2 1926.33
   474.2 1926.31   544.2 1926.39   623.3 1931.12   771.7 1943.03   781.6 1945.05
   801.4 1952.87   811.3 1957.31   821.2 1964.06   850.9 1975.88   890.5 1995.18
#Mann= 3 , 0 , 0
       0      .1       0   394.2    .045       0   474.2      .1       0
Bank Sta=394.2,474.2
XS Rating Curve= 0 ,0
Exp/Cntr=0.3,0.1

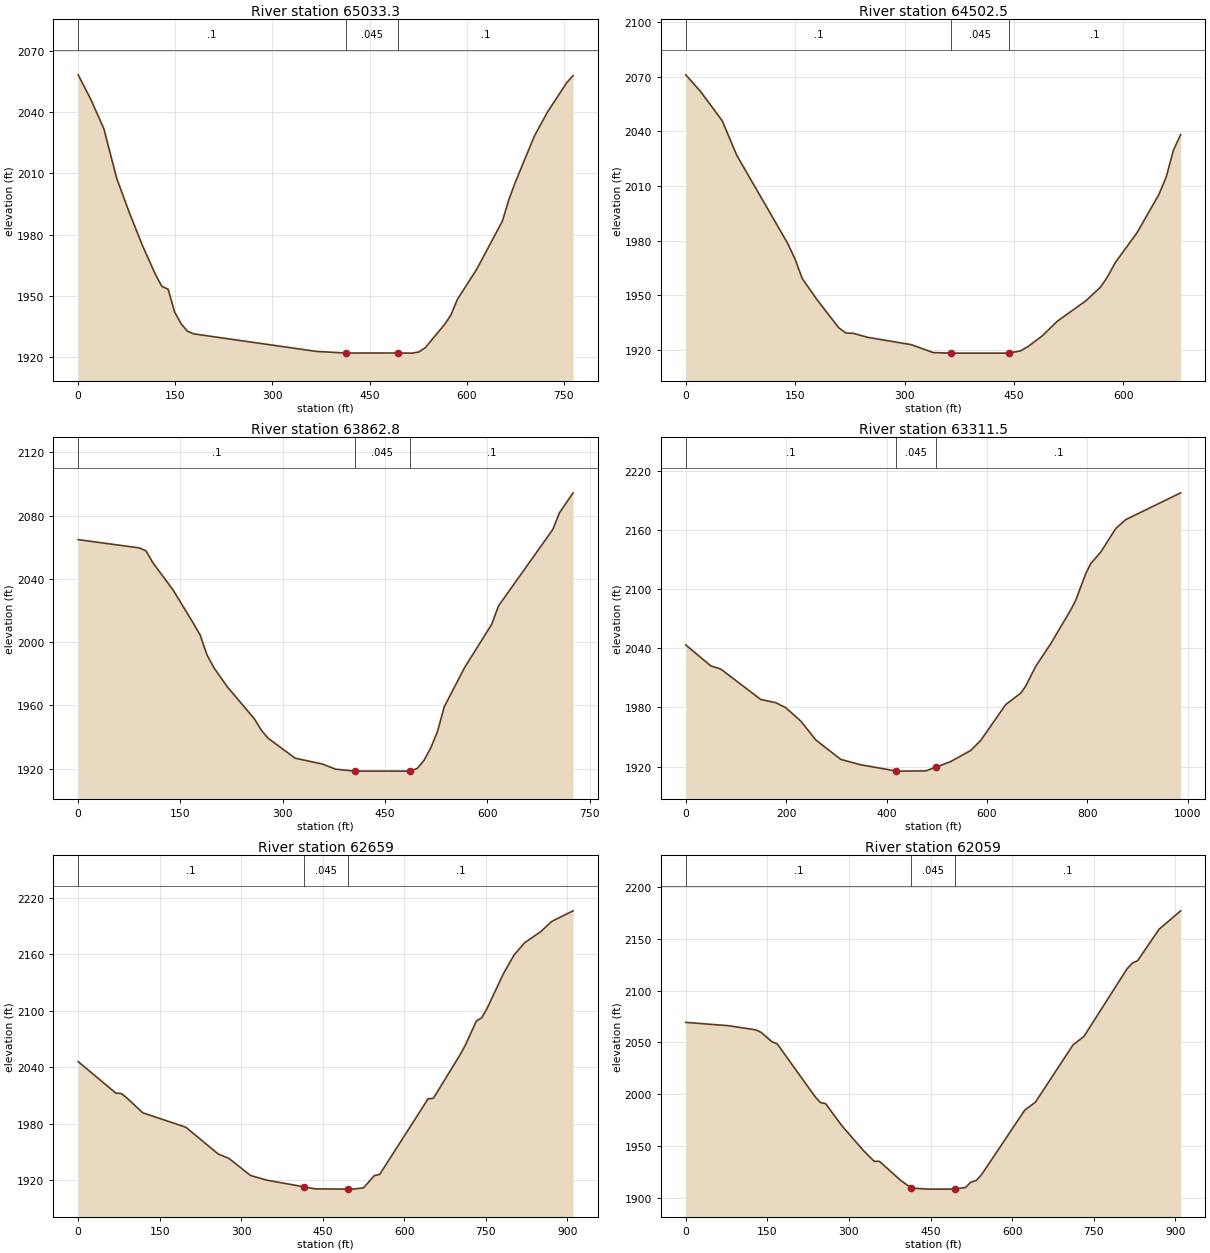
Type RM Length L Ch R = 1 ,65033.3 ,534.7,530.8,526.9
XS GIS Cut Line= 2
     1943042.742       174246.49     1942305.725       174044.48
#Sta/Elev= 30
       0 2058.32    19.8 2046.12    39.7 2031.88    59.6 2007.48    79.4 1990.42
    99.2  1974.7   119.1 1960.61     129 1954.68     139 1953.16   148.9 1942.06
   158.8 1936.36   168.7  1932.6   178.6 1931.29   367.2 1922.72   413.2  1921.9
   493.2 1921.92   516.1 1921.85     526 1922.43   535.9 1924.49   565.7 1935.86
   575.6 1940.56   585.6 1948.22   615.3 1962.91     655 1986.53     665 1997.04
   674.9 2005.57   704.6 2028.39   724.5 2039.95   754.3 2054.42   764.2 2057.94
#Mann= 3 , 0 , 0
       0      .1       0   413.2    .045       0   493.2      .1       0
Bank Sta=413.2,493.2
XS Rating Curve= 0 ,0
Exp/Cntr=0.3,0.1

Type RM Length L Ch R = 1 ,64502.5 ,642.4,639.7,637
XS GIS Cut Line= 2
     1943132.966      173692.356     1942467.554      173558.993
#Sta/Elev= 30
       0 2070.96      20 2061.99    49.9 2045.85    69.9 2026.87   139.7 1978.58
   149.7 1970.11   159.7  1959.3   179.6  1947.9   209.6 1932.36   219.6 1929.41
   229.5 1929.27   249.5 1927.05   309.4 1923.02   339.3 1918.68   363.8  1918.4
   439.1 1918.39   443.8 1918.47   459.1 1919.64   469.1 1921.95     489 1927.91
     509 1935.74   548.9 1947.17   568.9 1954.66   578.8 1960.57   588.8 1967.95
   618.8 1984.41   648.7 2005.32   658.7 2014.86   668.7 2029.66   678.6 2038.23
#Mann= 3 , 0 , 0
       0      .1       0   363.8    .045       0   443.8      .1       0
Bank Sta=363.8,443.8
XS Rating Curve= 0 ,0
Exp/Cntr=0.3,0.1

Type RM Length L Ch R = 1 ,63862.8 ,521.3,551.3,581.3
XS GIS Cut Line= 2
     1943247.891      173046.785     1942530.488      172938.648
#Sta/Elev= 30
       0 2064.83    89.4  2059.6    99.4 2057.75   109.3 2050.34   139.1 2033.03
     169 2011.84   178.9 2004.41   188.8 1991.97   198.8 1983.94   218.6 1971.74
   258.4 1951.42   268.3 1944.42   278.3 1939.26     318 1926.57   357.8 1922.88
   377.7 1919.57   405.9  1918.4     477 1918.37   485.9 1918.43   496.9 1920.01
   506.9  1925.1   516.8 1932.98   526.7 1943.37   536.7 1959.11   566.5 1983.89
   606.2 2011.24   616.2 2022.88   695.7 2071.18   705.6 2081.81   725.5 2094.43
#Mann= 3 , 0 , 0
       0      .1       0   405.9    .045       0   485.9      .1       0
Bank Sta=405.9,485.9
XS Rating Curve= 0 ,0
Exp/Cntr=0.3,0.1

Type RM Length L Ch R = 1 ,63311.5 ,597.4,652.6,708.6
XS GIS Cut Line= 2
     1943412.956      172791.896      1942651.86      172165.464
#Sta/Elev= 30
       0 2043.36    49.8 2022.18    69.7 2018.95   149.4  1988.1   179.2 1984.89
   199.1 1979.78     229 1966.28   258.9 1947.14   308.7  1927.4   348.5 1921.93
   419.3 1915.61   428.2  1915.5   477.9 1915.75   499.3 1919.66   527.7 1925.21
   567.6 1936.48   587.5 1946.66   637.2 1982.92   667.1 1994.46   677.1 2001.75
     697  2021.7   726.9 2044.58   766.7 2078.83   776.6 2088.47   796.6  2115.6
   806.5 2125.74   826.4 2137.34   856.3 2161.25   876.2 2170.32   985.7 2197.49
#Mann= 3 , 0 , 0
       0      .1       0   419.3    .045       0   499.3      .1       0
Bank Sta=419.3,499.3
XS Rating Curve= 0 ,0
Exp/Cntr=0.3,0.1

Type RM Length L Ch R = 1 ,62659   ,601.2,600,597.9
XS GIS Cut Line= 3
     1943572.292      172739.539     1943623.872      172286.466
     1943682.698      171835.463
#Sta/Elev= 30
       0 2045.94    69.4 2012.39    79.3 2012.03    89.2  2007.5     119 1991.48
   198.3 1976.09   257.7 1947.71   277.6  1942.9   317.2  1924.8     347 1919.81
     416  1912.7   436.2 1910.57     496 1910.29   505.4 1910.27   525.2  1911.6
     545 1924.65   554.9  1925.9   643.9 2006.27   653.8 2006.95   703.2 2053.54
   713.1    2064   732.8 2089.14   742.7 2092.57   752.6 2102.54   782.3 2139.07
   802.1 2159.22   821.8 2172.44   851.5 2184.28   871.3    2195   910.8 2206.33
#Mann= 3 , 0 , 0
       0      .1       0     416    .045       0     496      .1       0
Bank Sta=416,496
XS Rating Curve= 0 ,0
Exp/Cntr=0.3,0.1

Type RM Length L Ch R = 1 ,62059   ,592.3,600,607.7
XS GIS Cut Line= 3
     1944175.605      172824.007     1944217.091      172370.903
     1944258.577      171917.798
#Sta/Elev= 30
       0 2069.41    79.1 2066.17   128.6 2062.18   138.5  2059.8   158.3 2050.73
   168.2 2048.62   237.4 1997.83   247.3 1991.93   257.2 1990.75   286.8  1969.6
   326.4 1945.59   346.2 1935.09   356.1 1934.98   395.6 1916.41     415 1909.17
   445.1 1908.12     495  1908.2   514.4  1909.7   524.2  1914.9   534.1 1916.48
     544 1922.21   623.2 1984.48   642.9 1992.24   712.2 2047.72     732  2055.7
   811.1 2120.96     821 2126.74   830.9 2129.14   870.4 2159.55     910  2177.3
#Mann= 3 , 0 , 0
       0      .1       0     415    .045       0     495      .1       0
Bank Sta=415,495
XS Rating Curve= 0 ,0
Exp/Cntr=0.3,0.1

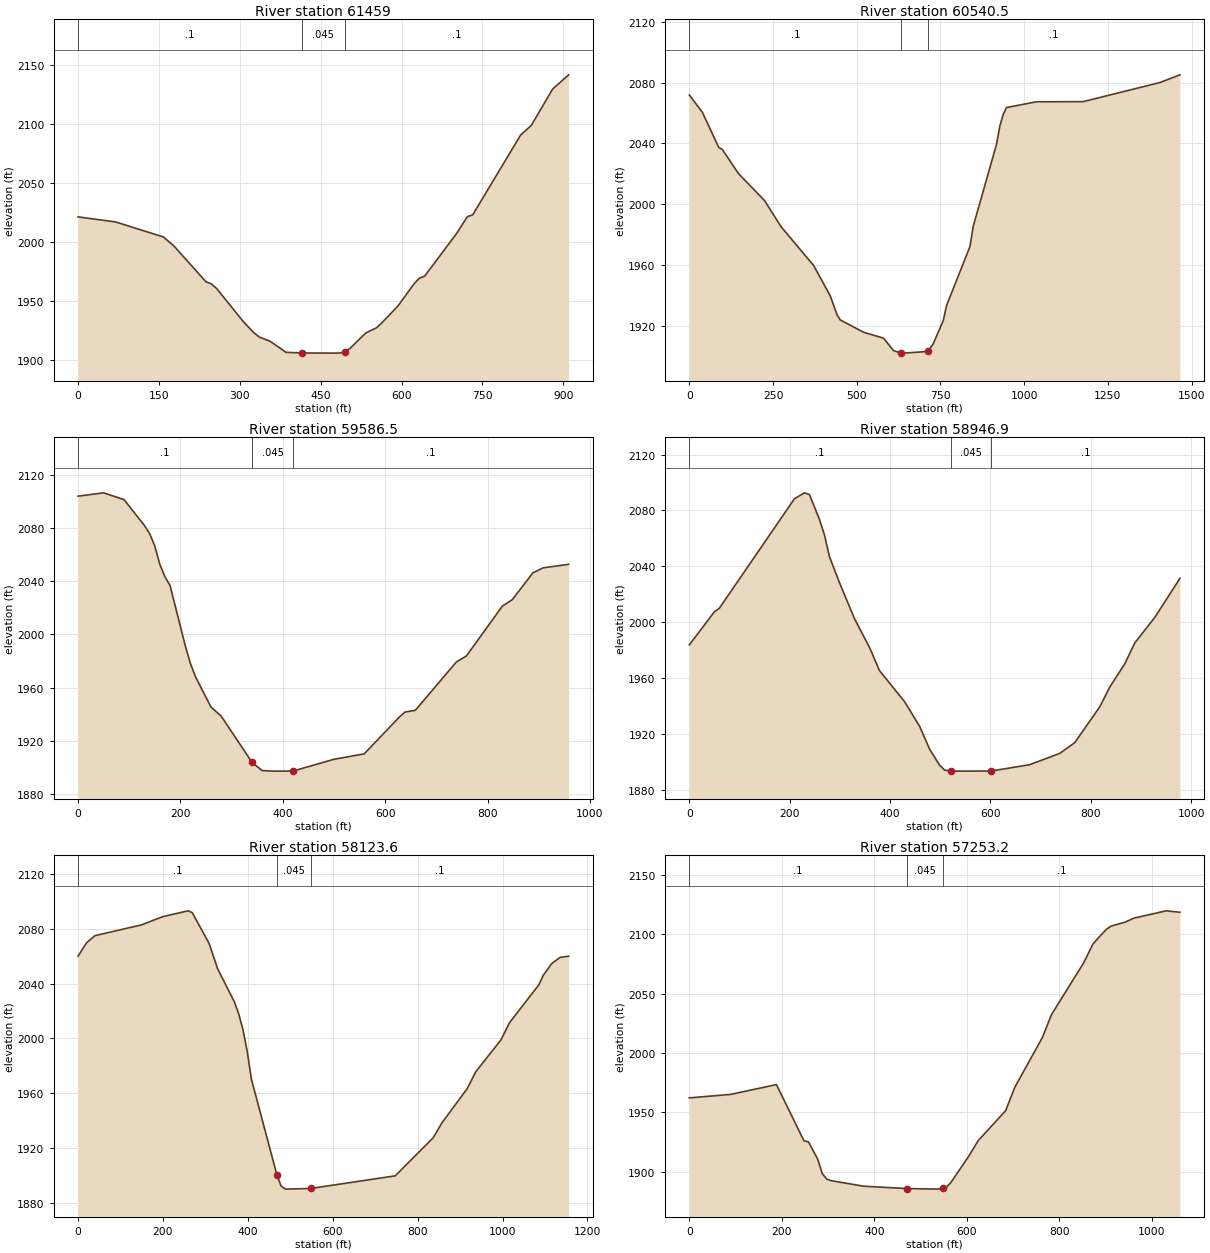
Type RM Length L Ch R = 1 ,61459   ,849.7,918.5,987.2
XS GIS Cut Line= 3
     1944703.077       172913.12     1944807.334      172470.226
     1944911.592      172027.331
#Sta/Elev= 30
       0  2021.4    69.2 2017.18   158.3  2004.4     178 1996.69   237.4  1966.4
   247.3 1964.62   257.2 1960.66   306.6 1932.63   326.4 1923.15   336.3 1919.57
   356.1 1916.08   385.8 1906.67     415 1906.09   484.7 1905.98     495 1907.14
   504.5 1910.03   534.1 1923.19   553.9 1927.51   563.8 1931.78   593.5    1946
   623.2 1964.67     633 1969.48   642.9 1971.19   702.3 2007.43   722.1 2021.57
     732 2023.12     821 2090.79   840.8 2098.94   880.3 2129.69     910 2141.77
#Mann= 3 , 0 , 0
       0      .1       0     415    .045       0     495      .1       0
Bank Sta=415,495
XS Rating Curve= 0 ,0
Exp/Cntr=0.3,0.1

Type RM Length L Ch R = 1 ,60540.5 ,1031.8,954,876.8
XS GIS Cut Line= 4
     1944998.382      173424.135     1945065.685      173059.043
     1945686.156      172979.105     1945591.756      172520.589
#Sta/Elev= 30
       0 2071.81    39.1 2060.37    87.9 2037.29    97.7 2036.24   146.5 2020.22
   224.7 2002.39   273.6 1985.32   371.2  1959.7   420.9 1939.75   440.8 1927.47
   450.7 1923.93   520.2 1915.82   579.8 1911.97   609.6 1903.78   632.6 1902.11
   639.4  1902.1   712.6  1903.2   728.7 1908.38   758.5 1923.65   768.4 1933.53
     838 1972.13   847.9 1985.55   917.4 2039.39   927.3 2051.39   937.3 2059.02
   947.2 2063.56  1036.7 2067.34  1176.1 2067.43  1405.2 2079.98    1465 2085.06
#Mann= 3 , 0 , 0
       0      .1       0   632.6    .045       0   712.6      .1       0
Bank Sta=632.6,712.6
XS Rating Curve= 0 ,0
Exp/Cntr=0.3,0.1

Type RM Length L Ch R = 1 ,59586.5 ,696,639.5,582.5
XS GIS Cut Line= 2
     1945789.547      174084.938     1945830.004      173127.449
#Sta/Elev= 30
       0 2103.92    49.9 2106.44    89.8 2101.32   129.8 2081.82   139.8 2075.79
   149.7 2066.65   159.7 2052.75   169.7 2043.35   179.7 2036.79   209.6 1991.26
   219.6 1978.01   229.6 1968.06   259.6  1945.5   279.5 1938.68   339.8 1903.92
   359.4 1897.74   379.3 1897.29   419.8 1897.32   499.1 1906.12     559 1910.28
   628.9 1938.46   638.9 1941.71   658.9 1943.02   738.7 1979.21   758.7 1983.87
   828.6  2021.2   848.5 2026.26   888.5 2046.31   908.4 2050.07   958.3 2052.73
#Mann= 3 , 0 , 0
       0      .1       0   339.8    .045       0   419.8      .1       0
Bank Sta=339.8,419.8
XS Rating Curve= 0 ,0
Exp/Cntr=0.3,0.1

Type RM Length L Ch R = 1 ,58946.9 ,870.4,823.3,776.2
XS GIS Cut Line= 2
     1946760.521      173666.879     1945951.376      173118.458
#Sta/Elev= 30
       0 1983.71    49.9 2007.37    59.8 2009.92   209.5 2088.33   229.4 2092.56
   239.4 2091.28   259.3 2073.48   269.3  2062.4   279.3 2046.75   299.2 2028.24
   329.2 2002.39   359.1  1981.8     379 1965.22   428.9 1943.06   458.8 1925.45
   478.8 1909.02   498.7 1897.54   508.7 1894.02   521.3 1893.32   528.6  1893.3
   601.3 1893.35   678.3 1897.92   738.1    1906     768 1913.71   817.9 1939.37
   837.8 1953.51   867.8 1970.22   887.7 1985.16   927.6 2003.41   977.5 2031.34
#Mann= 3 , 0 , 0
       0      .1       0   521.3    .045       0   601.3      .1       0
Bank Sta=521.3,601.3
XS Rating Curve= 0 ,0
Exp/Cntr=0.3,0.1

Type RM Length L Ch R = 1 ,58123.6 ,855.7,870.4,885
XS GIS Cut Line= 2
     1946922.351      172448.665     1945803.032      172736.362
#Sta/Elev= 30
       0 2060.02    19.9 2069.78    39.8 2075.02   149.4 2082.87   199.3 2088.88
     259 2093.14     269 2091.82   308.8 2069.28   328.8 2050.85   368.6 2026.46
   378.6 2017.76   388.6 2006.27   398.5 1990.55   408.5 1970.06   468.2 1900.64
   478.2 1892.29   488.2 1889.99   548.2 1890.48   747.2 1899.69   836.9 1927.59
   856.8 1938.18   916.6 1963.27   936.5 1975.46   996.3 1998.96  1016.2 2011.38
    1086 2039.35  1095.9 2046.06  1115.8 2054.64  1135.8  2059.2  1155.7 2060.02
#Mann= 3 , 0 , 0
       0      .1       0   468.2    .045       0   548.2      .1       0
Bank Sta=468.2,548.2
XS Rating Curve= 0 ,0
Exp/Cntr=0.3,0.1

Type RM Length L Ch R = 1 ,57253.2 ,696.7,756.3,815.9
XS GIS Cut Line= 2
      1946468.33      171927.216      1945407.45       171913.73
#Sta/Elev= 30
       0 1962.26    89.2 1965.18   188.4 1973.44   247.9 1926.16   257.8  1925.1
   277.6 1910.66   287.6  1898.4   297.5  1893.8   307.4 1892.46   376.8 1887.86
   469.7 1885.88   535.4 1885.38   549.7 1886.12   555.3 1886.96   565.2 1890.69
   604.8 1913.38   624.7 1926.21   684.2 1951.52     704 1971.24   763.5 2013.04
   783.3 2032.43   852.7 2075.86   872.6  2091.6   882.5 2096.14   902.3 2104.36
   912.2 2106.99     942 2110.26   961.8 2113.69  1031.2 2119.84    1061 2118.64
#Mann= 3 , 0 , 0
       0      .1       0   469.7    .045       0   549.7      .1       0
Bank Sta=469.7,549.7
XS Rating Curve= 0 ,0
Exp/Cntr=0.3,0.1

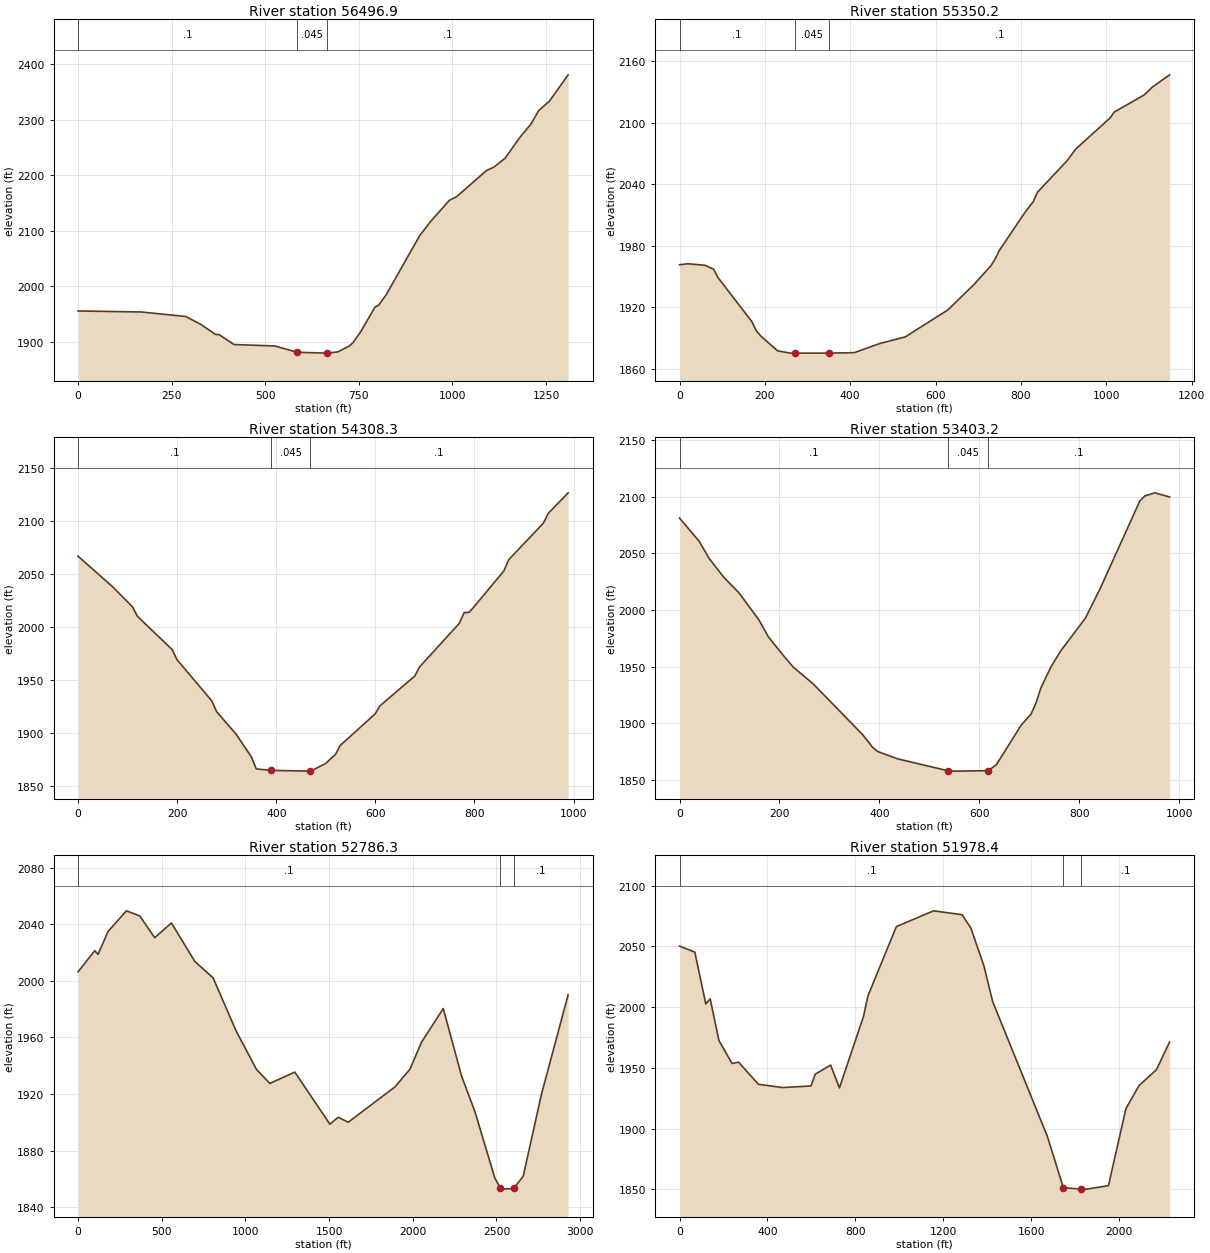
Type RM Length L Ch R = 1 ,56496.9 ,1059.4,1146.6,1233.9
XS GIS Cut Line= 3
     1946589.702      171873.273     1946045.776      170825.879
     1945933.395      170762.945
#Sta/Elev= 30
       0 1955.57   168.6 1953.78   287.6 1945.62   327.3  1931.6     367 1913.36
   376.9 1912.88   416.5 1895.07   525.6 1892.47   585.4  1881.1   664.5 1879.56
   665.4 1879.56   694.2 1881.84     724 1892.32   733.9 1898.08   753.8 1916.84
   793.4 1962.78   803.3  1966.3   823.2 1985.04   912.4  2091.3   942.2 2117.36
   991.8  2155.1  1011.6 2161.93    1091 2208.88  1110.8    2215  1140.5 2230.94
  1180.2 2268.68  1209.9 2292.79  1229.8 2316.38  1259.5 2334.34    1309 2381.36
#Mann= 3 , 0 , 0
       0      .1       0   585.4    .045       0   665.4      .1       0
Bank Sta=585.4,665.4
XS Rating Curve= 0 ,0
Exp/Cntr=0.3,0.1

Type RM Length L Ch R = 1 ,55350.2 ,1015.3,1042,1068.7
XS GIS Cut Line= 2
     1946778.502      172026.111      1947794.43      171491.176
#Sta/Elev= 30
       0  1961.6      20 1962.59    59.9 1961.09    79.9 1957.31    89.9 1949.24
   169.7 1906.06   179.7 1897.43   189.7 1892.39   229.6  1877.7   259.6  1875.4
   270.2  1875.4   350.2  1875.4   409.3 1875.86   469.2 1884.75   529.2 1891.28
     629 1917.65   688.9 1941.98   728.8 1960.28   738.8  1966.6   748.8 1975.24
   808.7 2012.34   828.7 2023.13   838.6 2032.34   908.5 2063.33   928.5 2074.61
  1008.4 2104.67  1018.4 2110.54  1088.2 2127.18  1108.2 2135.08  1148.2  2146.9
#Mann= 3 , 0 , 0
       0      .1       0   270.2    .045       0   350.2      .1       0
Bank Sta=270.2,350.2
XS Rating Curve= 0 ,0
Exp/Cntr=0.3,0.1

Type RM Length L Ch R = 1 ,54308.3 ,864.4,905.1,945.8
XS GIS Cut Line= 2
     1947079.684       172803.79      1948068.64      172799.295
#Sta/Elev= 30
       0 2066.62    69.9 2037.77   109.9 2018.91   119.9 2009.94   189.8 1978.65
   199.8 1969.05   269.7 1930.39   279.7 1920.07   319.7 1898.44   349.6 1877.55
   359.6  1866.2   388.6 1864.78   468.6 1864.08   469.5 1864.07   499.5 1871.24
   519.5 1879.89   529.4 1888.42   599.4 1917.96   609.4 1925.68   679.3 1953.59
   689.3 1962.32   769.2 2003.27   779.2 2013.47   789.2 2013.74   799.2 2019.06
   859.1  2052.6   869.1 2063.33     939 2097.76     949 2107.07     989 2126.34
#Mann= 3 , 0 , 0
       0      .1       0   388.6    .045       0   468.6      .1       0
Bank Sta=388.6,468.6
XS Rating Curve= 0 ,0
Exp/Cntr=0.3,0.1

Type RM Length L Ch R = 1 ,53403.2 ,629.2,616.8,604.4
XS GIS Cut Line= 2
     1946908.865      173275.792     1947641.591      173927.604
#Sta/Elev= 30
       0 2081.14    39.6 2060.47    59.4 2045.37    89.2 2028.55   118.9 2015.11
   158.5 1991.49   178.3 1975.96     208 1959.71   227.8 1949.46   267.5 1934.74
   366.5 1889.87   386.3 1878.77   396.2 1875.08   435.9 1868.63     538 1857.95
   554.7  1857.7     618 1858.12     634 1863.34   683.5 1898.16   703.3 1907.99
   713.2 1917.74   723.1 1931.09   742.9 1949.45   762.8 1963.84   812.3 1992.82
     842 2019.12   921.2 2096.26   931.2 2100.66     951 2103.39   980.7 2099.73
#Mann= 3 , 0 , 0
       0      .1       0     538    .045       0     618      .1       0
Bank Sta=538,618
XS Rating Curve= 0 ,0
Exp/Cntr=0.3,0.1

Type RM Length L Ch R = 1 ,52786.3 ,889.3,807.8,726.3
XS GIS Cut Line= 3
     1945101.773      175509.933     1946529.487      173859.735
     1947183.075      174219.795
#Sta/Elev= 30
       0 2006.33    99.6 2021.24   119.6 2018.64   179.4 2034.88     289 2049.45
   368.7 2045.83   458.3 2030.48     558 2040.86   697.5 2013.73   807.1 2002.01
   946.6 1963.96  1066.1 1937.34  1145.8 1927.43  1295.3 1935.41  1504.6 1898.61
  1554.4 1903.52  1614.2 1899.98  1893.1 1924.93  1982.8 1937.41  2052.6  1956.6
  2182.1 1980.38  2291.5 1932.64  2371.1 1907.53  2490.5 1860.46  2522.9 1853.55
  2540.3 1852.69  2602.9 1853.18  2659.7 1861.79  2769.1 1919.93  2928.3  1990.1
#Mann= 3 , 0 , 0
       0      .1       0  2522.9    .045       0  2602.9      .1       0
Bank Sta=2522.9,2602.9
XS Rating Curve= 0 ,0
Exp/Cntr=0.3,0.1

Type RM Length L Ch R = 1 ,51978.4 ,816.1,762.3,708.5
XS GIS Cut Line= 3
     1945708.632       175986.43     1946637.928      175041.572
     1947156.104       174300.71
#Sta/Elev= 30
       0  2050.2    69.8 2045.28   119.6 2002.62   139.5 2006.85   179.4 1972.45
   239.2 1953.62     269 1954.72   358.7 1936.52   468.3 1933.81   597.9 1935.12
   617.8 1944.85   687.6 1952.31   727.4 1933.48     837 1992.38   856.9 2009.11
   986.5 2066.26  1155.9 2079.24  1285.4 2076.04  1325.3 2065.07  1384.9 2033.86
  1424.6  2004.5    1673 1893.78  1746.1 1851.39  1826.1 1850.27  1851.8 1850.22
  1951.2 1853.06  2030.7 1916.48  2090.3 1935.45  2169.8 1948.52  2229.4  1971.3
#Mann= 3 , 0 , 0
       0      .1       0  1746.1    .045       0  1826.1      .1       0
Bank Sta=1746.1,1826.1
XS Rating Curve= 0 ,0
Exp/Cntr=0.3,0.1