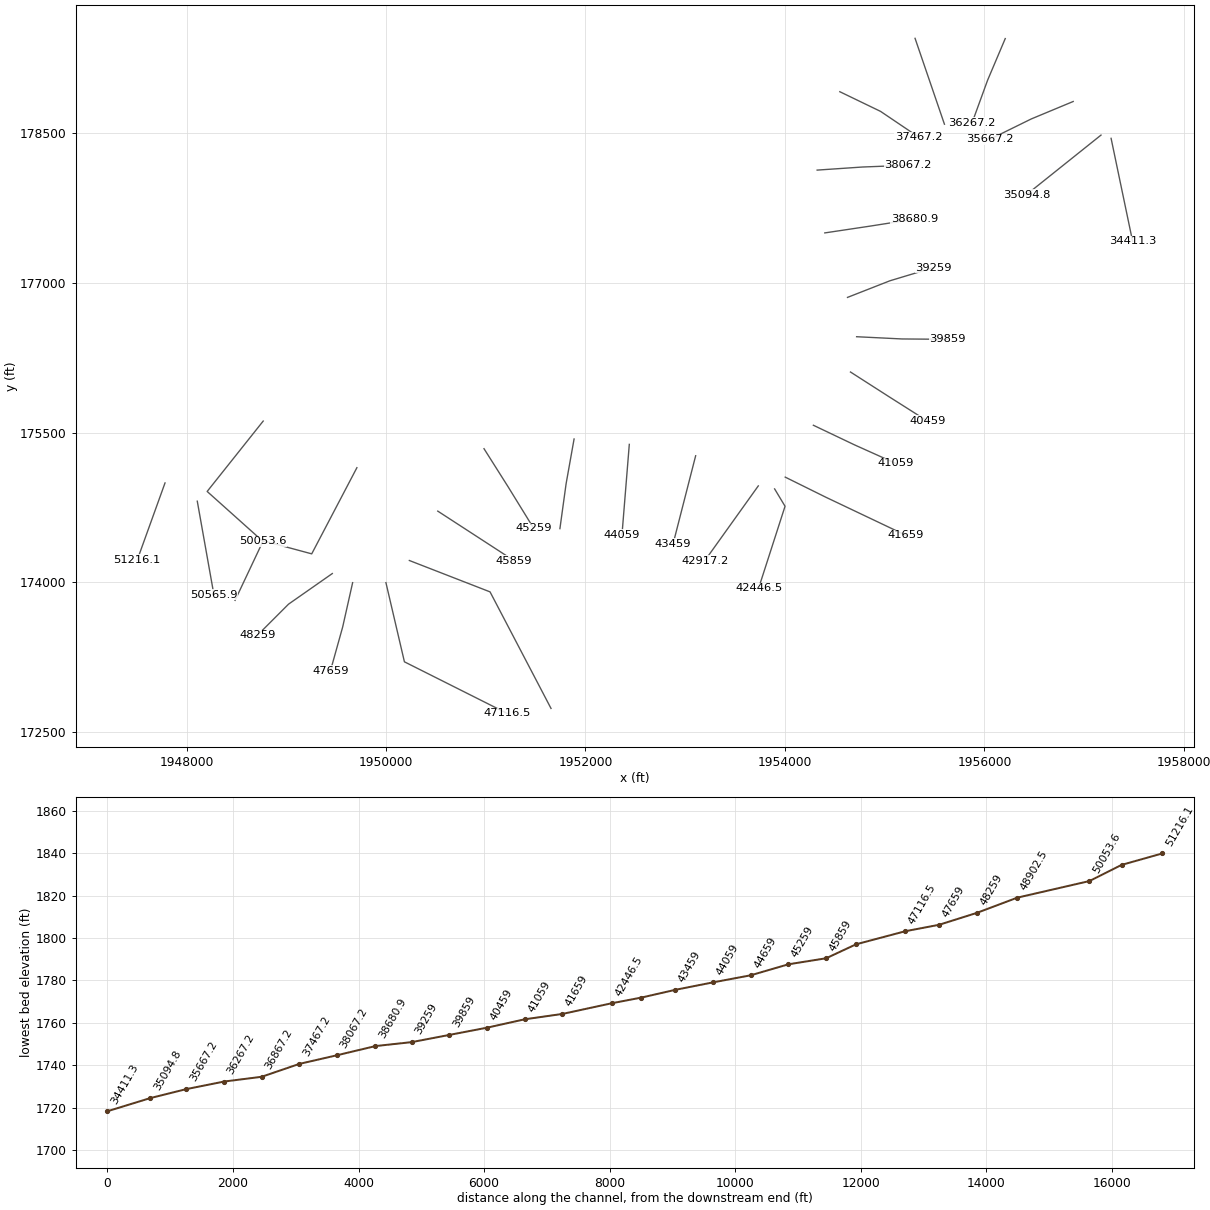
HEC-RAS study BlstnRvr.prj: BlstnRvr

--- BlstnRvr.g01 (geometry) --- (continued)

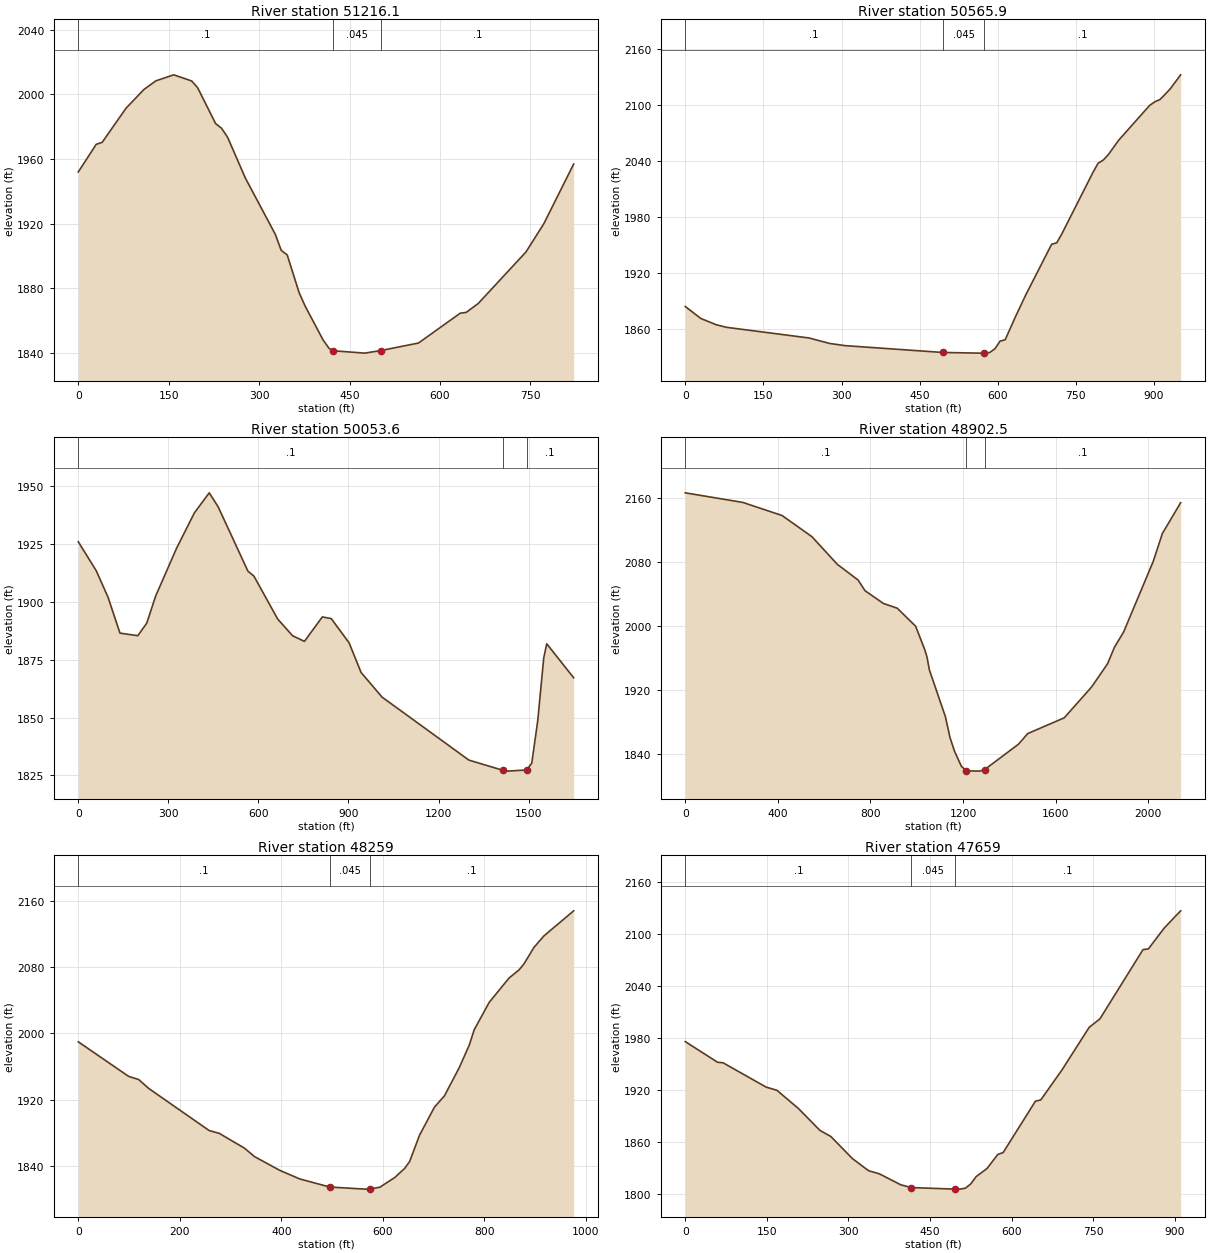
Type RM Length L Ch R = 1 ,51216.1 ,621.4,650.2,678.9
XS GIS Cut Line= 2
     1947783.941      174995.976     1947505.235      174222.792
#Sta/Elev= 30
       0    1952    29.7 1969.07    39.6 1970.31    79.2 1991.43   108.9 2003.02
   128.7 2008.37   158.4 2012.09   188.1 2008.29     198 2004.13   227.8 1981.93
   237.6 1979.06   247.6 1973.54   277.3 1948.12   326.8 1913.44   336.7 1903.45
   346.6 1900.67   366.4 1877.28   376.3 1869.01     406 1848.12   415.9 1842.86
   422.1 1841.34   475.3 1839.86   502.1 1841.46   564.4  1846.1   633.7 1864.58
   643.6 1865.07   663.4 1870.52   742.7 1902.42   772.4 1919.95   821.9 1956.87
#Mann= 3 , 0 , 0
       0      .1       0   422.1    .045       0   502.1      .1       0
Bank Sta=422.1,502.1
XS Rating Curve= 0 ,0
Exp/Cntr=0.3,0.1

Type RM Length L Ch R = 1 ,50565.9 ,475.7,512.3,548.9
XS GIS Cut Line= 2
     1948107.398      174812.925     1948273.923      173876.657
#Sta/Elev= 30
       0 1884.34    29.7 1871.53    59.4 1864.82    79.2 1862.04   237.7 1850.62
   277.4 1844.75   307.1 1842.43     494 1835.15   564.6 1834.43     574 1834.44
   584.4 1835.08   594.4 1839.05   604.3 1847.22   614.2 1848.79     634 1873.51
   653.8 1896.88   703.3 1950.85   713.2 1952.48   723.1 1962.23   782.6 2027.72
   792.5 2037.58   802.4 2040.96   812.3 2046.91   832.1 2062.25   891.5 2099.49
   901.4 2103.29   911.3 2105.75   921.2 2111.33   931.2  2117.3     951 2132.18
#Mann= 3 , 0 , 0
       0      .1       0     494    .045       0     574      .1       0
Bank Sta=494,574
XS Rating Curve= 0 ,0
Exp/Cntr=0.3,0.1

Type RM Length L Ch R = 1 ,50053.6 ,1302.1,1151.1,1000.1
XS GIS Cut Line= 3
     1948768.401      175616.321     1948206.495      174910.566
     1948763.906      174411.593
#Sta/Elev= 30
       0 1925.99    59.5 1913.52    99.1    1902   138.8 1886.49   198.3 1885.38
     228  1890.8   257.8 1902.55   327.1 1923.12   386.6 1938.46   436.2 1947.15
   465.9  1941.1   565.1 1913.27   584.9 1911.17   664.2 1892.58   713.8 1885.36
   753.4 1882.92   812.9  1893.5   842.6 1892.77   902.1  1882.3     942 1869.49
  1011.8 1858.84  1301.1  1831.6  1413.5 1827.21  1430.8 1826.82  1493.5 1827.32
  1510.6 1830.25  1530.5 1848.58  1550.5 1875.76  1560.5 1881.88  1650.2 1867.19
#Mann= 3 , 0 , 0
       0      .1       0  1413.5    .045       0  1493.5      .1       0
Bank Sta=1413.5,1493.5
XS Rating Curve= 0 ,0
Exp/Cntr=0.3,0.1

Type RM Length L Ch R = 1 ,48902.5 ,595.5,643.7,701.5
XS GIS Cut Line= 4
     1949707.909      175148.814      1949254.88      174284.908
     1948768.401      174416.088     1948486.208      173818.603
#Sta/Elev= 30
       0 2166.33   248.8 2154.33   418.1 2138.03   547.5  2111.5     657 2077.03
   746.5 2057.51   776.4 2044.21     856 2028.23   915.8 2022.32   995.2 1999.82
  1034.8  1970.4  1044.6 1961.03  1054.5 1945.39  1123.7 1887.04  1143.4 1861.12
  1163.2 1843.81  1192.8 1825.06  1213.6 1819.37  1271.9 1818.97  1293.6 1820.96
  1439.8 1852.65  1479.3 1865.82  1637.1 1885.49  1755.5 1924.04  1824.5 1953.05
  1854.1 1973.61  1893.6 1992.55  2021.8 2080.83  2061.2  2115.6  2140.1    2154
#Mann= 3 , 0 , 0
       0      .1       0  1213.6    .045       0  1293.6      .1       0
Bank Sta=1213.6,1293.6
XS Rating Curve= 0 ,0
Exp/Cntr=0.3,0.1

Type RM Length L Ch R = 1 ,48259   ,558.8,599.8,628.3
XS GIS Cut Line= 3
     1949461.451      174087.532     1949022.607      173780.646
     1948710.918      173468.959
#Sta/Elev= 30
       0 1989.86    99.2 1948.08     119 1944.25   138.8 1933.49   257.8 1882.65
   277.7 1879.23   327.2 1861.45   347.1  1851.2   396.7  1834.6   436.3 1824.14
   495.5 1814.33   564.9 1811.79   575.5 1811.98   594.3 1814.11   623.7 1825.84
   643.2 1836.83     653 1845.19   672.6 1877.07     702 1910.97   721.6 1924.51
     751 1958.87   770.6 1985.99   780.4 2004.56   809.8 2037.51     849    2067
   868.6 2076.75   878.3    2084   897.9 2103.83   917.5 2117.78   976.3  2148.2
#Mann= 3 , 0 , 0
       0      .1       0   495.5    .045       0   575.5      .1       0
Bank Sta=495.5,575.5
XS Rating Curve= 0 ,0
Exp/Cntr=0.3,0.1

Type RM Length L Ch R = 1 ,47659   ,517.6,542.4,570.1
XS GIS Cut Line= 3
     1949665.137      173996.108     1949565.269       173551.46
     1949443.001      173113.329
#Sta/Elev= 30
       0 1976.18    59.4 1952.37    69.4 1951.81   148.6 1923.75   168.4  1920.1
     208  1899.1   247.7 1873.76   267.5  1866.9   307.1 1841.45   336.8 1827.44
   356.6 1823.87   396.3 1811.12   415.7 1807.99   495.7  1806.2   505.2 1806.19
   515.1 1807.34   524.9 1812.28   534.8 1820.72   554.6 1829.88   574.4 1846.13
   584.3 1848.31   643.6 1907.52   653.5 1909.01     693 1944.05   742.5 1992.66
   762.3 2002.48   841.4 2082.22   851.3 2083.05   880.9 2107.44   910.6 2126.91
#Mann= 3 , 0 , 0
       0      .1       0   415.7    .045       0   495.7      .1       0
Bank Sta=415.7,495.7
XS Rating Curve= 0 ,0
Exp/Cntr=0.3,0.1

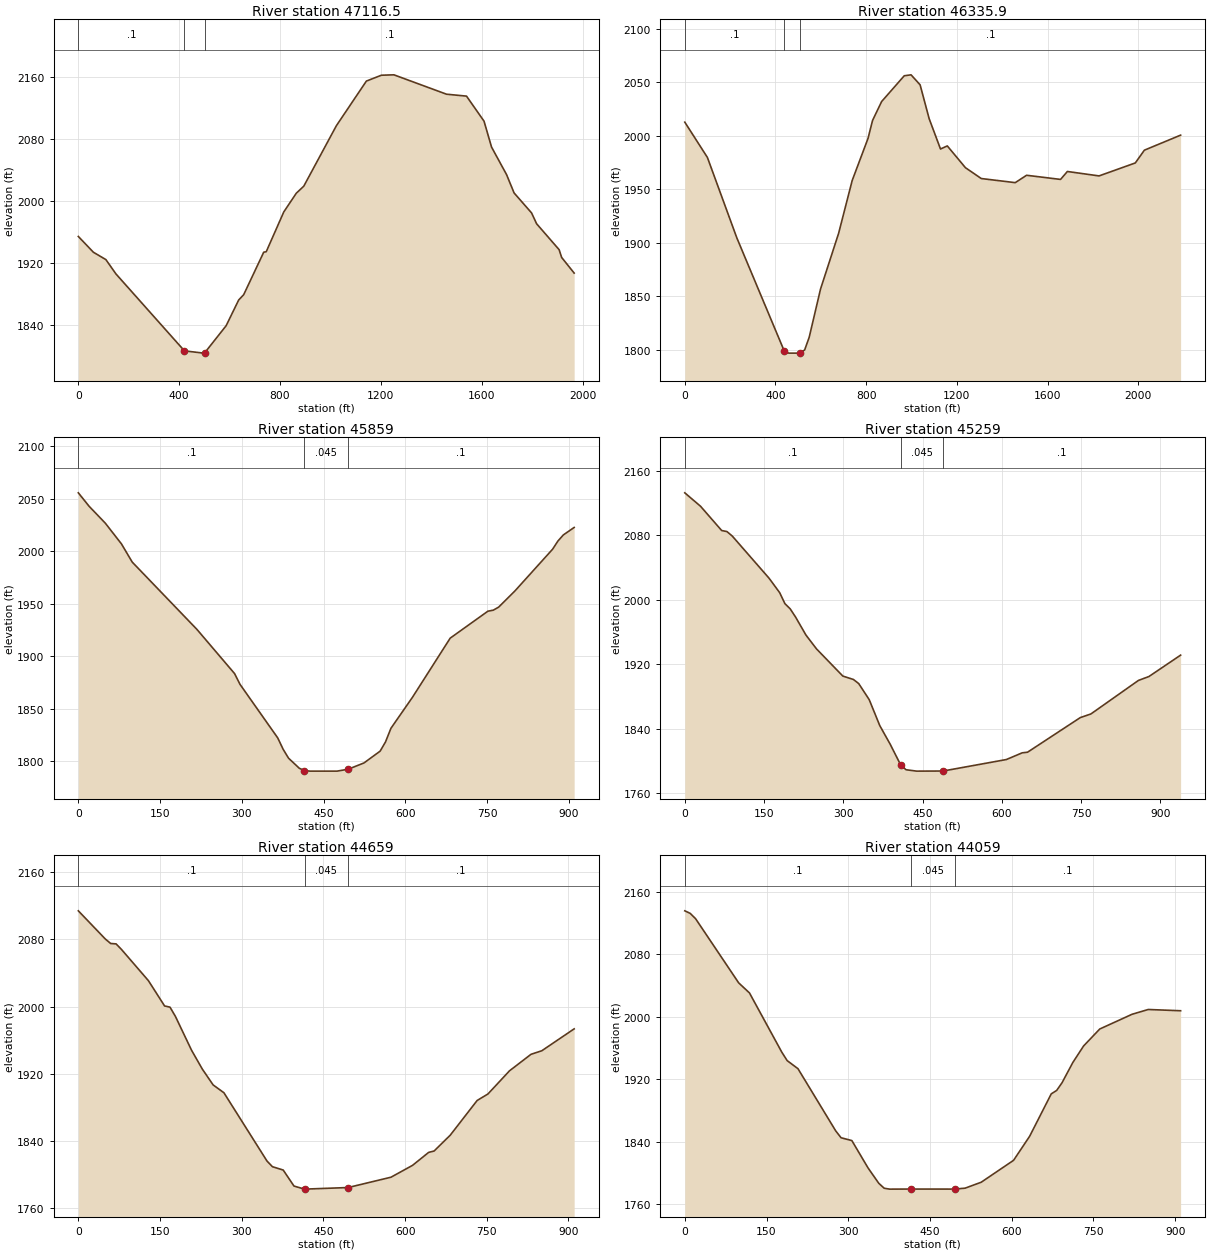
Type RM Length L Ch R = 1 ,47116.5 ,726.9,780.7,834.5
XS GIS Cut Line= 3
     1949999.055      173996.014     1950184.406      173202.369
     1951213.819      172685.415
#Sta/Elev= 30
       0 1953.93    59.6 1933.56   109.3    1924   149.1 1905.54   420.9 1806.05
     497 1803.13   500.9 1803.34   586.4 1838.59   636.1  1871.8     656 1878.66
   735.5 1933.61   745.4 1934.17     815 1985.61   864.6 2009.78   894.4 2018.93
  1023.5 2096.98  1142.7 2154.74  1202.3 2162.32  1251.9 2162.82  1460.5 2137.78
  1539.9 2135.29  1609.4  2102.9  1639.2 2069.44  1698.8 2033.84  1728.6 2010.17
  1798.1 1984.28    1818 1970.32  1907.3 1936.82  1917.3 1926.78  1966.9  1906.6
#Mann= 3 , 0 , 0
       0      .1       0   420.9    .045       0   500.9      .1       0
Bank Sta=420.9,500.9
XS Rating Curve= 0 ,0
Exp/Cntr=0.3,0.1

Type RM Length L Ch R = 1 ,46335.9 ,488.2,476.9,465.6
XS GIS Cut Line= 3
     1950233.854      174218.297     1951042.999      173903.629
     1951654.354      172734.863
#Sta/Elev= 30
       0 2012.62    99.8 1979.64   229.5  1904.6   439.1 1798.76     459 1796.98
   508.9 1796.98   528.9 1800.04   548.8 1811.79   598.7 1856.74   678.6 1908.88
   738.4 1958.13   808.3 1997.48   828.3 2014.24   868.2 2031.83   968.1 2055.92
   998.1  2056.8    1038 2047.47    1078  2015.8    1128 1987.54    1158 1990.43
  1237.9 1970.12  1307.8 1959.98  1457.7 1956.14  1507.7 1963.02  1657.6 1959.15
  1687.6 1966.56  1827.4 1962.43  1987.3 1974.53  2027.3 1986.45  2187.2 2000.49
#Mann= 3 , 0 , 0
       0      .1       0   439.1    .045       0   508.9      .1       0
Bank Sta=439.1,508.9
XS Rating Curve= 0 ,0
Exp/Cntr=0.3,0.1

Type RM Length L Ch R = 1 ,45859   ,623.9,600,575.5
XS GIS Cut Line= 3
     1950518.811      174713.379      1950900.38      174465.528
     1951281.949      174217.677
#Sta/Elev= 30
       0 2055.78    19.8 2042.95    49.5 2026.85    79.1 2007.12    98.9 1989.74
   217.6 1925.59   286.8 1883.38   296.7 1873.18     366 1822.06   375.9 1811.25
   385.8 1802.75   405.5 1793.16     415 1790.86   425.3  1790.4   474.8  1790.4
     495 1792.17   524.2 1798.18   553.9 1809.46   563.8 1818.26   573.7 1831.21
   613.3 1860.85   682.5  1917.2   751.7 1942.91   761.6 1943.88   771.5 1946.83
   801.2 1962.16   870.4    2002   880.3 2009.86   890.2 2015.64     910 2022.76
#Mann= 3 , 0 , 0
       0      .1       0     415    .045       0     495      .1       0
Bank Sta=415,495
XS Rating Curve= 0 ,0
Exp/Cntr=0.3,0.1

Type RM Length L Ch R = 1 ,45259   ,641,600,561.8
XS GIS Cut Line= 3
     1950982.403      175339.253     1951222.387      174959.924
     1951479.261       174542.95
#Sta/Elev= 30
       0 2132.46    29.9 2115.74    69.8 2085.75    79.8 2084.42    89.8 2078.94
   159.6 2026.58   179.6 2008.74   189.5 1995.14   199.5 1988.66   209.5 1978.72
   229.4 1956.14   249.4    1939   299.2 1905.34   319.2 1901.15   329.2 1896.08
   349.1 1876.15   369.1 1843.98     389 1820.68   408.9 1794.89   418.9 1789.26
   438.9 1787.56   488.9 1787.69   608.8 1801.94   638.8 1810.25   648.8 1810.99
   748.7 1853.91   768.7 1858.38   858.7 1899.94   878.6 1904.81   938.6 1931.31
#Mann= 3 , 0 , 0
       0      .1       0   408.9    .045       0   488.9      .1       0
Bank Sta=408.9,488.9
XS Rating Curve= 0 ,0
Exp/Cntr=0.3,0.1

Type RM Length L Ch R = 1 ,44659   ,594.7,600,603.1
XS GIS Cut Line= 3
     1951885.561      175436.701     1951805.621      174988.341
     1951743.511      174537.677
#Sta/Elev= 30
       0 2114.02    49.5 2080.47    59.4 2075.08    69.3 2074.63    79.2 2068.02
   128.7 2030.79   158.4 2000.65   168.3 1999.24   178.2 1988.31   207.9 1947.88
   227.7 1925.38   247.5 1906.56   267.3 1897.24   346.5 1815.78   356.4 1809.11
   376.2 1805.11     396 1786.02   415.4 1782.38   495.4 1784.28   574.1 1796.58
   613.7 1810.73   643.3 1826.18   653.2 1827.77   682.9 1846.68   732.3 1888.04
   752.1 1895.76   791.7 1923.37   831.2 1943.05     851 1947.27   910.4 1973.36
#Mann= 3 , 0 , 0
       0      .1       0   415.4    .045       0   495.4      .1       0
Bank Sta=415.4,495.4
XS Rating Curve= 0 ,0
Exp/Cntr=0.3,0.1

Type RM Length L Ch R = 1 ,44059   ,609.4,600,590.6
XS GIS Cut Line= 3
     1952439.255      175382.635     1952402.486      174929.124
     1952365.716      174475.612
#Sta/Elev= 30
       0 2135.68     9.9 2132.42    19.8  2125.6    98.9 2043.36   118.7 2030.46
     178 1954.61   187.9  1943.7   207.7  1933.4     277 1853.66   286.8 1844.87
   306.6 1841.26   336.3 1806.24   356.1 1786.43     366 1780.17   375.9 1779.04
     415 1779.14     495 1779.08   514.4 1780.26     544 1787.87   603.4 1815.95
     633 1846.89   672.6 1901.17   682.5 1905.49   692.4 1915.42   712.2 1941.36
     732 1962.57   761.6 1984.24     821 2003.14   850.6 2009.24     910 2007.63
#Mann= 3 , 0 , 0
       0      .1       0     415    .045       0     495      .1       0
Bank Sta=415,495
XS Rating Curve= 0 ,0
Exp/Cntr=0.3,0.1

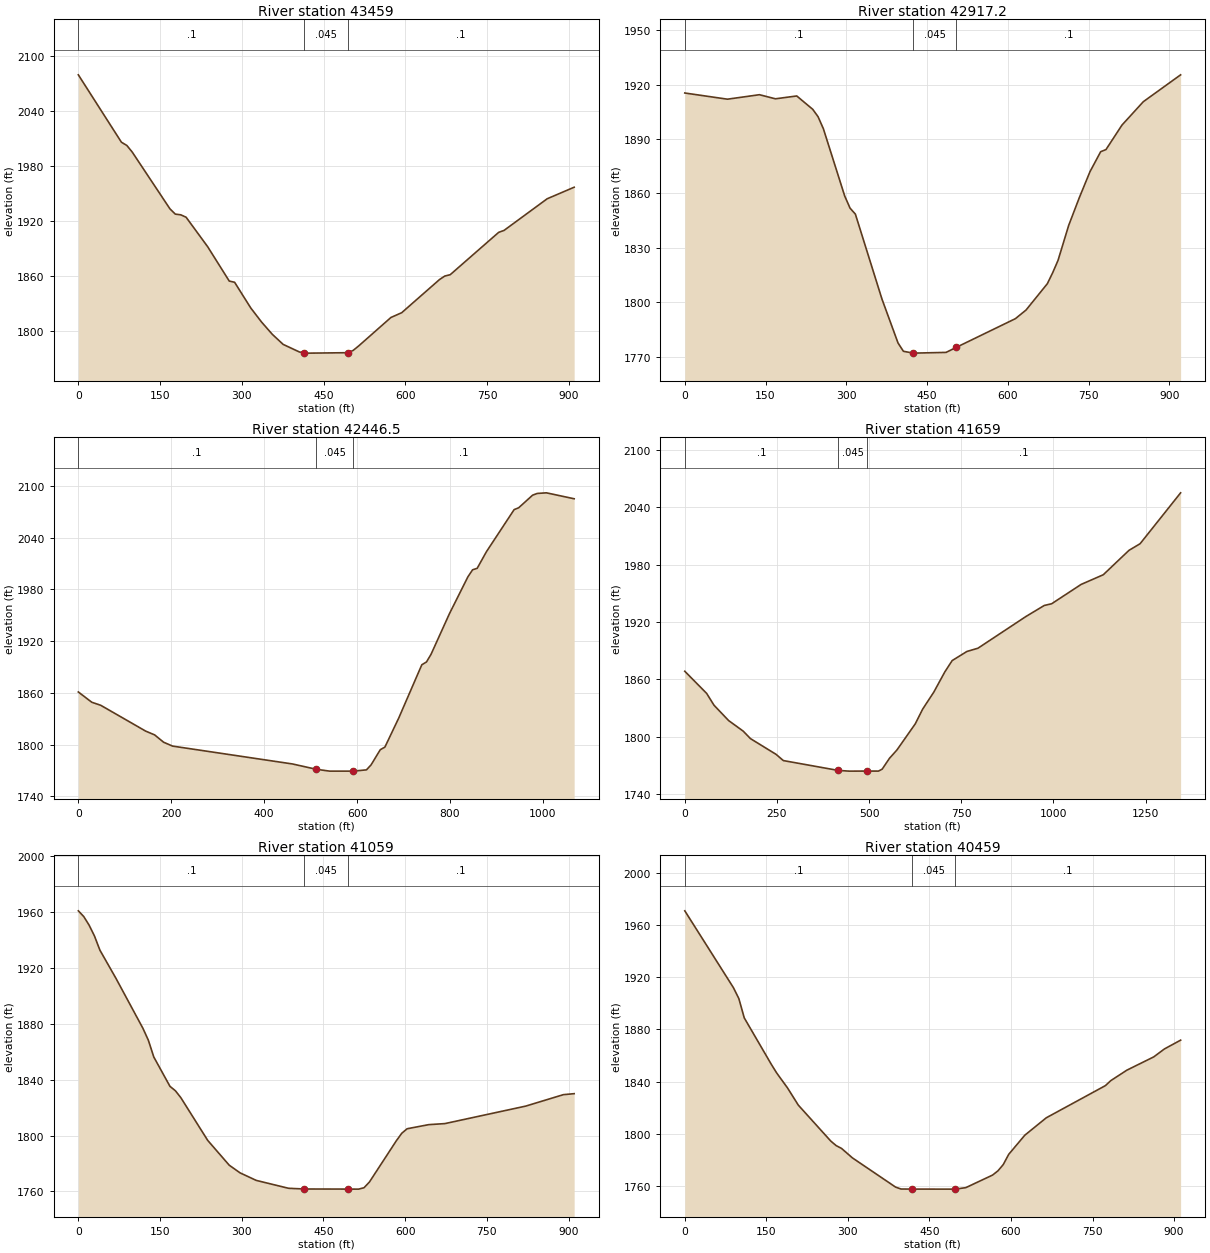
Type RM Length L Ch R = 1 ,43459   ,563.1,541.8,520.4
XS GIS Cut Line= 3
     1953104.603       175268.64     1952991.692      174827.872
      1952878.78      174387.104
#Sta/Elev= 30
       0 2079.04    79.1 2005.53      89 2002.02    98.9 1994.82   168.2 1932.84
     178 1927.13   187.9 1926.38   197.8 1923.75   237.4 1891.57     277 1854.11
   286.8 1852.82   316.5 1824.75   336.3 1809.42   356.1 1795.98   375.9 1785.06
   405.5 1776.84     415 1775.59   425.3 1775.53     495    1776   504.5 1778.53
   514.4 1783.31   573.7  1814.4   593.5 1819.62   662.7 1855.67   672.6 1859.59
   682.5 1861.05   771.5 1907.26   781.4 1909.39   860.5 1943.87     910 1956.46
#Mann= 3 , 0 , 0
       0      .1       0     415    .045       0     495      .1       0
Bank Sta=415,495
XS Rating Curve= 0 ,0
Exp/Cntr=0.3,0.1

Type RM Length L Ch R = 1 ,42917.2 ,453.5,470.6,487.8
XS GIS Cut Line= 2
     1953732.577      174966.192     1953196.922      174217.217
#Sta/Elev= 30
       0 1915.37    79.2 1911.96   138.6 1914.43   168.3 1912.17   207.9 1913.74
   237.6 1906.37   247.5  1902.3   257.4 1895.63     297 1858.52   306.9 1851.85
   316.8 1848.55   366.3 1801.57     396 1777.46     406 1772.89   424.4 1771.87
   485.2 1772.27   504.4 1775.08   613.9 1790.87   633.7 1795.63   673.3 1810.18
   683.2 1816.23   693.1    1823   712.9 1842.32   732.7 1857.67   752.5 1871.98
   772.3 1882.98   782.2 1884.17   811.9 1897.68   851.5 1910.57   920.8  1925.4
#Mann= 3 , 0 , 0
       0      .1       0   424.4    .045       0   504.4      .1       0
Bank Sta=424.4,504.4
XS Rating Curve= 0 ,0
Exp/Cntr=0.3,0.1

Type RM Length L Ch R = 1 ,42446.5 ,707.3,787.6,868.7
XS GIS Cut Line= 3
      1953896.31      174936.139     1954000.876      174762.222
     1953735.656      173939.591
#Sta/Elev= 30
       0 1860.97      29 1849.05    48.3 1845.52     145 1815.58   164.3  1811.2
   183.6  1802.7   202.9 1798.21   461.2 1777.49   511.6 1771.41   540.7  1769.2
   591.6  1769.2   620.2 1770.66   630.1 1776.41     650 1794.06   659.9 1797.05
   689.7 1830.75   739.4 1892.54   749.4 1895.77   759.3 1904.73     799 1951.93
   838.8 1994.69   848.7 2002.63   858.6 2004.38   878.5 2023.65   938.1  2072.4
     948  2074.6   977.8 2089.15   987.8 2091.16  1007.6 2091.88  1067.3 2084.99
#Mann= 3 , 0 , 0
       0      .1       0   511.6    .045       0   591.6      .1       0
Bank Sta=511.6,591.6
XS Rating Curve= 0 ,0
Exp/Cntr=0.3,0.1

Type RM Length L Ch R = 1 ,41659   ,599.2,600,601.2
XS GIS Cut Line= 3
     1954002.773       175054.19     1954411.067      174852.193
     1955214.595      174470.031
#Sta/Elev= 30
       0 1868.58    59.4 1845.39    79.2  1833.1   118.8 1817.07   158.4    1806
   178.2 1798.14   247.6 1781.71   267.4 1775.18   415.5 1764.93   445.6 1764.15
   495.5  1764.2   525.5 1764.18   535.5  1766.2   555.5 1777.64   575.5 1786.22
   625.5 1813.71   645.5 1829.07   675.5  1846.7   705.5 1867.92   725.5 1879.77
   765.4 1889.29   795.4 1892.68   925.4 1925.81   975.4 1937.41   995.4 1939.19
  1075.4 1959.42  1135.4 1969.51  1205.3 1995.08  1235.3 2001.96  1345.3  2055.2
#Mann= 3 , 0 , 0
       0      .1       0   415.5    .045       0   495.5      .1       0
Bank Sta=415.5,495.5
XS Rating Curve= 0 ,0
Exp/Cntr=0.3,0.1

Type RM Length L Ch R = 1 ,41059   ,607,600,592.1
XS GIS Cut Line= 3
      1954285.04      175574.311     1954695.885      175378.465
      1955110.83      175191.854
#Sta/Elev= 30
       0 1961.01     9.9 1956.94    19.8 1950.75    29.7 1942.92    39.6 1932.85
    69.3 1912.47   118.7 1876.73   128.6 1868.24   138.5  1856.3   168.2 1835.26
   178.1 1832.12     188 1827.24   237.5 1796.53     277 1778.76   296.8 1773.29
   326.5 1767.88   385.9 1762.22   415.1 1761.71   495.1 1761.65   514.5 1761.62
   524.4 1762.62   534.3 1766.71   583.7 1796.26   593.6 1801.62   603.5 1804.87
   643.1 1807.82   672.7 1808.56   821.1 1821.09   890.3  1829.3   910.1 1830.01
#Mann= 3 , 0 , 0
       0      .1       0   415.1    .045       0   495.1      .1       0
Bank Sta=415.1,495.1
XS Rating Curve= 0 ,0
Exp/Cntr=0.3,0.1

Type RM Length L Ch R = 1 ,40459   ,571.3,600,630.7
XS GIS Cut Line= 3
     1954656.924      176108.364     1955041.908      175861.448
     1955425.826      175618.029
#Sta/Elev= 30
       0  1970.9    89.5 1911.99    99.4 1903.68   109.4 1888.86   159.1 1853.31
     169 1846.67   188.9 1835.24   208.8 1822.03   268.4 1794.54   278.4 1791.02
   288.3 1788.86   308.2 1781.64   387.8  1759.2   397.7 1757.76   417.4  1757.7
     487 1757.67   497.4 1757.71   516.7 1758.77   566.1 1768.43     576 1771.68
   585.8  1776.5   595.7 1784.27   625.4 1798.98   664.9 1812.32   773.6 1836.96
   783.5 1840.78   813.1 1848.81   862.5 1858.97   882.3  1865.1     912 1871.81
#Mann= 3 , 0 , 0
       0      .1       0   417.4    .045       0   497.4      .1       0
Bank Sta=417.4,497.4
XS Rating Curve= 0 ,0
Exp/Cntr=0.3,0.1

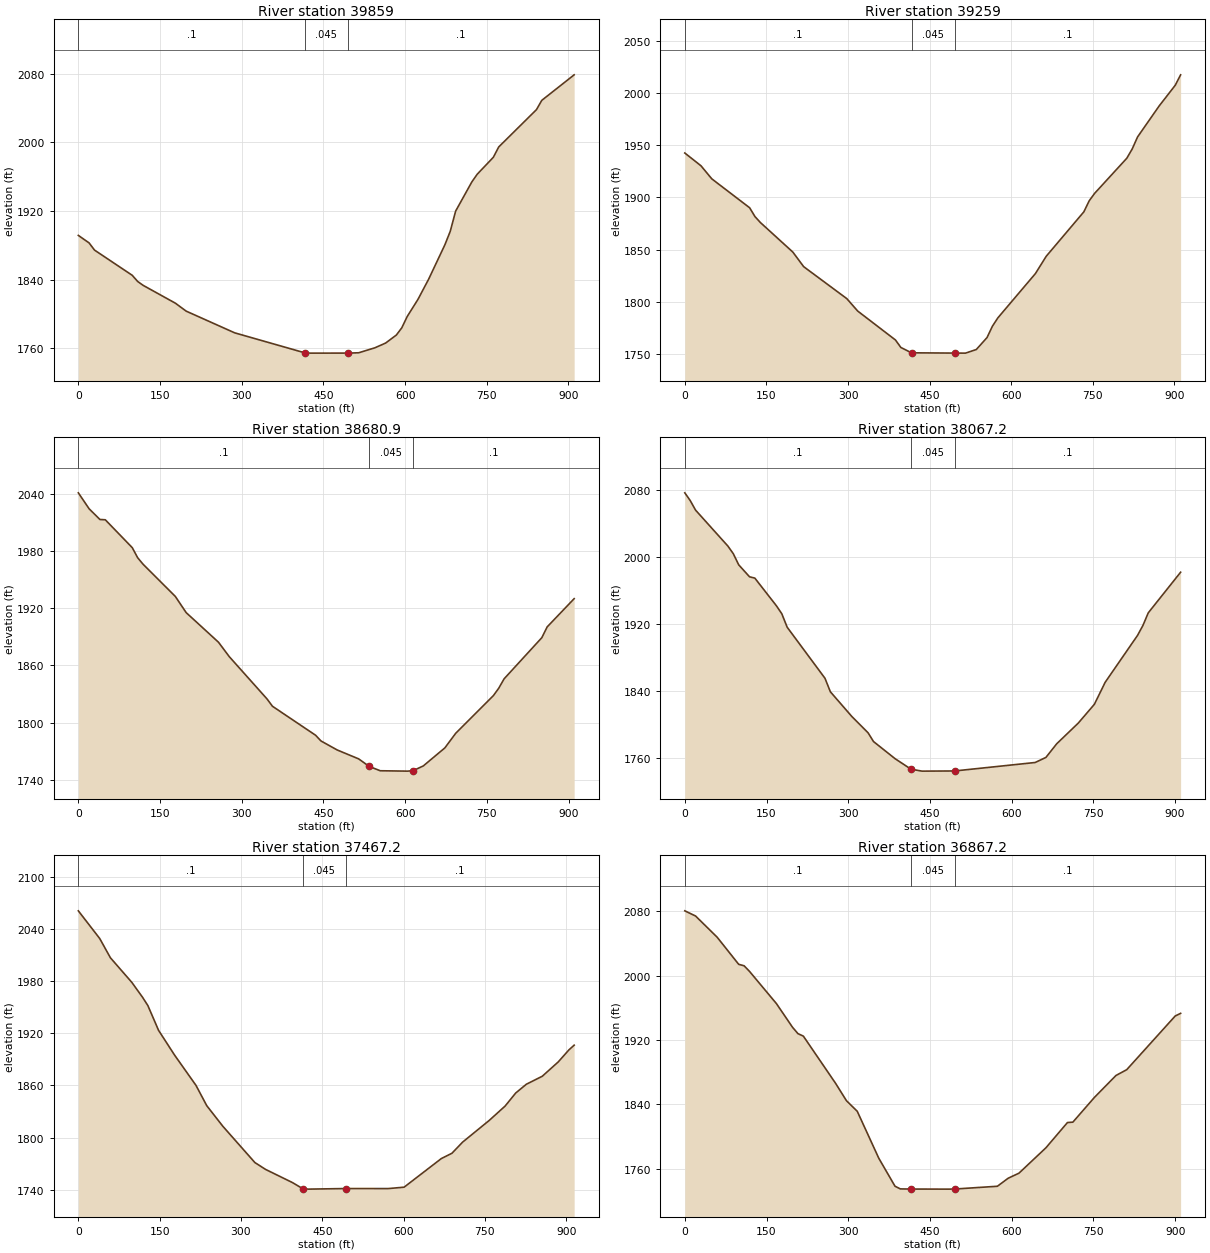
Type RM Length L Ch R = 1 ,39859   ,576.7,600,616.6
XS GIS Cut Line= 3
     1954718.551       176462.07      1955173.47      176439.722
     1955628.373      176436.094
#Sta/Elev= 30
       0 1891.46    19.8 1882.67    29.7 1874.35      99 1844.94   108.9 1837.81
   118.8 1833.31   178.2 1812.46     198  1803.2   287.1  1777.9   415.5 1754.67
   425.8 1754.26   495.5  1754.3   514.8 1754.67   544.5 1760.46   564.2 1765.98
     584 1775.38   593.9 1783.74   603.8 1796.86   623.6 1816.88   643.4 1840.66
     673 1880.46   682.9 1896.23   692.8 1919.78   722.5 1953.73   732.4 1962.74
     762 1982.47   771.9 1994.52   841.2 2038.02     851 2048.86   910.4 2078.58
#Mann= 3 , 0 , 0
       0      .1       0   415.5    .045       0   495.5      .1       0
Bank Sta=415.5,495.5
XS Rating Curve= 0 ,0
Exp/Cntr=0.3,0.1

Type RM Length L Ch R = 1 ,39259   ,590.8,578.1,569.8
XS GIS Cut Line= 3
     1954627.124      176856.348     1955052.444      177022.984
      1955487.77      177154.238
#Sta/Elev= 30
       0 1942.47    29.8 1930.21    49.6 1917.74   119.2 1890.04   129.1 1881.53
     139 1875.89   198.6 1847.62   218.5 1833.67   297.9 1803.01   317.8 1791.17
   387.3 1763.43   397.2 1756.28   416.8 1751.15   496.8  1750.9   516.1 1750.86
   535.9 1754.31   555.6 1765.75   565.5 1776.61   575.4 1784.54   644.6 1827.05
   664.4 1843.57   733.6 1886.14   743.4 1896.67   753.3 1903.76   812.6 1937.48
   822.5 1946.35   832.4 1957.88   871.9 1987.41   901.6 2007.33   911.5 2017.32
#Mann= 3 , 0 , 0
       0      .1       0   416.8    .045       0   496.8      .1       0
Bank Sta=416.8,496.8
XS Rating Curve= 0 ,0
Exp/Cntr=0.3,0.1

Type RM Length L Ch R = 1 ,38680.9 ,618.9,613.6,606.8
XS GIS Cut Line= 3
     1954399.523       177502.97     1954849.742      177570.458
     1955299.039      177641.146
#Sta/Elev= 30
       0  2041.3    19.8 2024.55    39.6 2013.31    49.5 2012.99      99 1983.71
   108.9 1973.13   118.8 1966.34   178.1 1932.44   197.9 1915.51   257.3 1884.36
   277.1  1869.2   346.4 1824.78   356.3 1817.14   435.5 1786.68   445.4 1780.67
     475 1771.25   514.6 1761.84   533.7    1754   554.1 1749.38   603.6 1748.99
   613.7 1749.27   633.2 1754.45   672.8  1773.4   692.6 1788.68   761.8 1828.26
   771.6    1836   781.5 1845.92   850.8 1889.19   860.6 1900.49   910.1 1930.13
#Mann= 3 , 0 , 0
       0      .1       0   533.7    .045       0   613.7      .1       0
Bank Sta=533.7,613.7
XS Rating Curve= 0 ,0
Exp/Cntr=0.3,0.1

Type RM Length L Ch R = 1 ,38067.2 ,628.7,600,565
XS GIS Cut Line= 3
     1954322.628      178132.766      1954776.81      178163.666
     1955231.424      178181.379
#Sta/Elev= 30
       0 2077.21     9.9 2068.02    19.8 2056.52    79.2 2013.53    89.1 2004.39
      99 1991.13   118.8  1976.9   128.6 1975.28   168.2 1942.22   178.1 1932.69
     188 1916.56   257.3 1855.65   267.2 1839.51   306.8 1809.83   336.5 1790.42
   346.4 1780.02     386 1759.55   415.2 1746.97   435.4 1744.66   495.2 1744.85
   643.2 1754.97   662.9 1761.04   682.7 1777.31   722.3 1802.04   751.9 1824.53
   771.7 1850.82   831.1 1906.84     841 1918.72   850.8  1933.8   910.2 1982.36
#Mann= 3 , 0 , 0
       0      .1       0   415.2    .045       0   495.2      .1       0
Bank Sta=415.2,495.2
XS Rating Curve= 0 ,0
Exp/Cntr=0.3,0.1

Type RM Length L Ch R = 1 ,37467.2 ,643.8,600,564.1
XS GIS Cut Line= 3
     1954550.006       178918.73     1954958.835      178721.342
     1955340.816      178463.706
#Sta/Elev= 30
       0 2060.98    39.5 2029.07    59.2 2006.92    98.7 1978.62   118.4 1961.52
   128.3 1951.89     148 1923.41   177.6 1894.85   217.1 1859.99   236.9 1836.68
   266.5 1813.01   325.7 1771.17   345.4 1763.29   394.8 1748.19     414 1741.14
   424.4 1740.58     494 1741.25   571.6 1741.21     601 1742.82   669.6 1775.74
   689.3 1781.91   708.9 1794.68   757.9 1819.61   787.3 1836.19   806.9 1851.24
   826.5 1861.33   855.9 1870.54   885.3    1887   904.9 1900.79   914.7  1906.3
#Mann= 3 , 0 , 0
       0      .1       0     414    .045       0     494      .1       0
Bank Sta=414,494
XS Rating Curve= 0 ,0
Exp/Cntr=0.3,0.1

Type RM Length L Ch R = 1 ,36867.2 ,640.5,600,562.4
XS GIS Cut Line= 3
      1955304.49      179453.967     1955451.804      179023.474
     1955599.117      178592.982
#Sta/Elev= 30
       0 2080.69    19.8 2074.25    59.4 2047.87    98.9 2014.16   108.8 2012.34
   118.7 2005.43   168.2 1965.26   197.8 1935.76   207.7 1927.92   217.6 1924.84
     277 1865.86   296.7  1844.5   316.5 1831.34   356.1 1772.86   385.8 1738.11
   395.6 1734.78     415 1734.58   484.7  1734.5     495  1734.6   573.7 1738.07
   593.5 1748.06   613.3 1754.34   662.7 1785.86   702.3 1817.35   712.2  1817.8
   751.7 1848.52   791.3 1875.84   811.1  1883.1   900.1 1949.89     910 1953.16
#Mann= 3 , 0 , 0
       0      .1       0     415    .045       0     495      .1       0
Bank Sta=415,495
XS Rating Curve= 0 ,0
Exp/Cntr=0.3,0.1

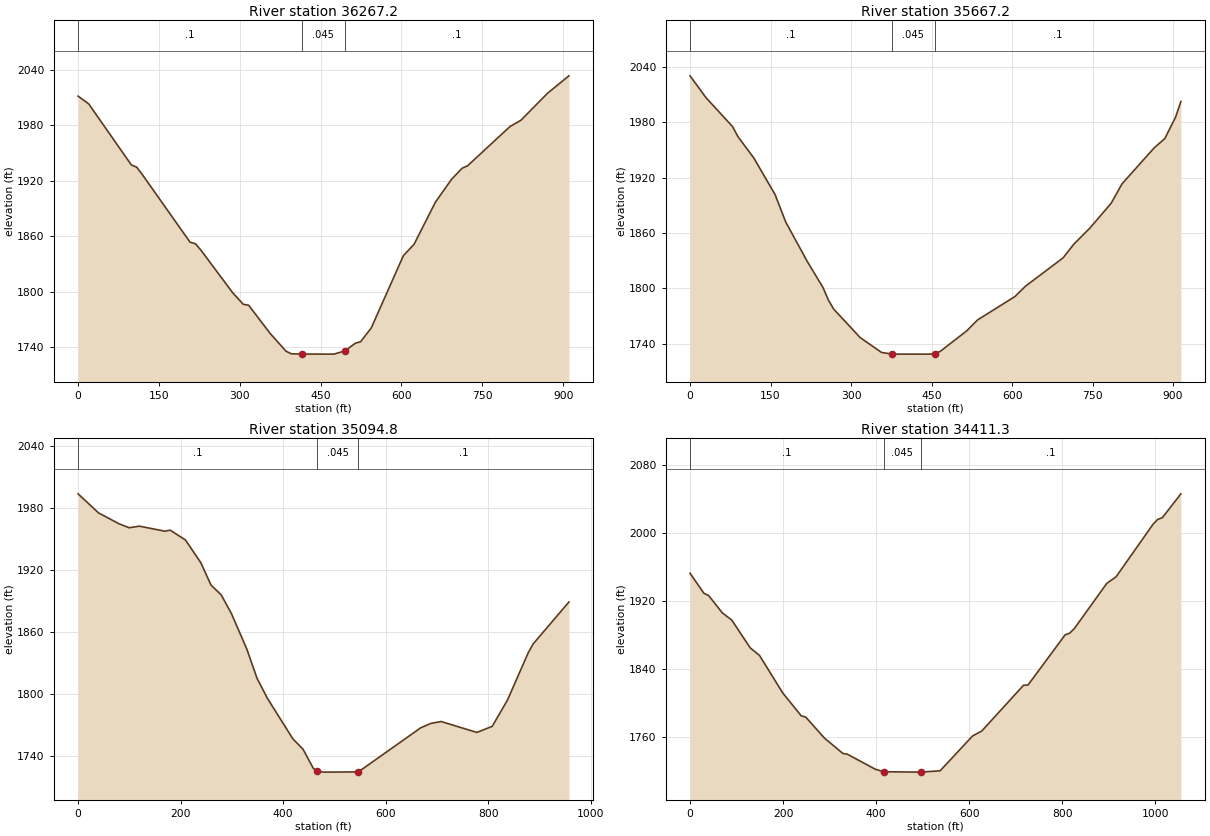
Type RM Length L Ch R = 1 ,36267.2 ,643,600,557.7
XS GIS Cut Line= 3
     1956208.782      179451.492     1956031.352      179032.652
     1955875.298      178604.479
#Sta/Elev= 30
       0 2011.58    19.8 2003.13    98.9 1937.03   108.8 1934.66   118.7 1927.06
   207.7 1853.49   217.6 1851.76   227.4 1845.23   286.8 1798.75   306.5 1786.19
   316.4 1785.23     356 1754.88   385.6 1735.51   395.5 1732.61   414.9  1732.3
   474.7 1732.25   494.9 1735.73   514.3    1744   524.2  1745.7     544 1760.69
   603.5 1838.86   623.3 1851.15   662.9 1896.74   692.6  1921.3   712.5 1933.56
   722.4 1936.08   801.6 1978.82   821.4 1985.38     871 2014.74   910.6 2033.57
#Mann= 3 , 0 , 0
       0      .1       0   414.9    .045       0   494.9      .1       0
Bank Sta=414.9,494.9
XS Rating Curve= 0 ,0
Exp/Cntr=0.3,0.1

Type RM Length L Ch R = 1 ,35667.2 ,557.1,572.4,584.2
XS GIS Cut Line= 3
      1956890.14      178820.754     1956469.454      178645.579
     1956057.752       178443.13
#Sta/Elev= 30
       0 2030.32    29.7 2006.67    79.2  1975.3    89.2 1964.48   118.9  1941.2
   158.5  1901.6   178.3 1871.83   217.9 1829.68   247.7 1800.87   257.6 1787.55
   267.5 1777.59     317 1746.62   356.6 1730.59   376.4  1728.7   445.8 1728.69
   455.7  1729.1   465.7 1731.48   515.5  1753.9   535.5 1765.68   605.3 1791.09
   625.2  1802.4   695.1 1833.06     715 1847.83   744.9 1865.23   784.8 1892.35
   804.8 1913.23   864.6 1952.14   884.6 1962.36   904.5 1985.37   914.5 2002.47
#Mann= 3 , 0 , 0
       0      .1       0   376.4    .045       0   455.7      .1       0
Bank Sta=376.4,455.7
XS Rating Curve= 0 ,0
Exp/Cntr=0.3,0.1

Type RM Length L Ch R = 1 ,35094.8 ,622.3,683.6,744.9
XS GIS Cut Line= 2
     1957168.906       178483.73     1956420.953      177885.913
#Sta/Elev= 30
       0 1994.11    39.9 1975.65    79.8 1965.12    99.7 1961.24   119.7 1962.78
   169.6 1957.89   179.5 1958.94   209.4 1949.44   239.4 1927.41   259.3 1905.76
   279.3 1896.15   299.2 1878.06   329.1 1843.79   349.1 1815.44     369 1796.25
   418.9  1756.8   438.9 1746.62   458.8  1728.2   466.8 1725.51   478.8 1724.47
   546.8 1724.68   668.3 1767.38   688.2 1771.68   708.2 1773.51     778 1762.94
   807.9 1768.82   837.8 1794.44   877.7 1839.63   887.7 1848.66   957.5 1889.32
#Mann= 3 , 0 , 0
       0      .1       0   466.8    .045       0   546.8      .1       0
Bank Sta=466.8,546.8
XS Rating Curve= 0 ,0
Exp/Cntr=0.3,0.1

Type RM Length L Ch R = 1 ,34411.3 ,490.5,521.6,552.8
XS GIS Cut Line= 2
     1957270.082      178451.319     1957485.821      177418.355
#Sta/Elev= 30
       0 1952.56    29.9 1928.86    39.8 1926.35    69.7 1905.71    89.6 1897.45
   129.4 1864.63   149.3 1855.74   199.1 1811.71   238.9 1784.67   248.9 1782.98
   288.7 1758.48   328.5  1740.3   338.5 1739.29   398.2 1721.69   416.5 1718.73
   496.5 1718.26   537.6 1719.82   607.3 1760.82   627.2 1766.72   716.8 1820.51
   726.7 1820.93   806.4 1880.01   816.3    1882   826.3 1887.48     896 1940.68
   915.9 1948.32   995.5 2010.35  1005.5 2016.03  1015.4 2017.96  1055.2 2046.09
#Mann= 3 , 0 , 0
       0      .1       0   416.5    .045       0   496.5      .1       0
Bank Sta=416.5,496.5
XS Rating Curve= 0 ,0
Exp/Cntr=0.3,0.1