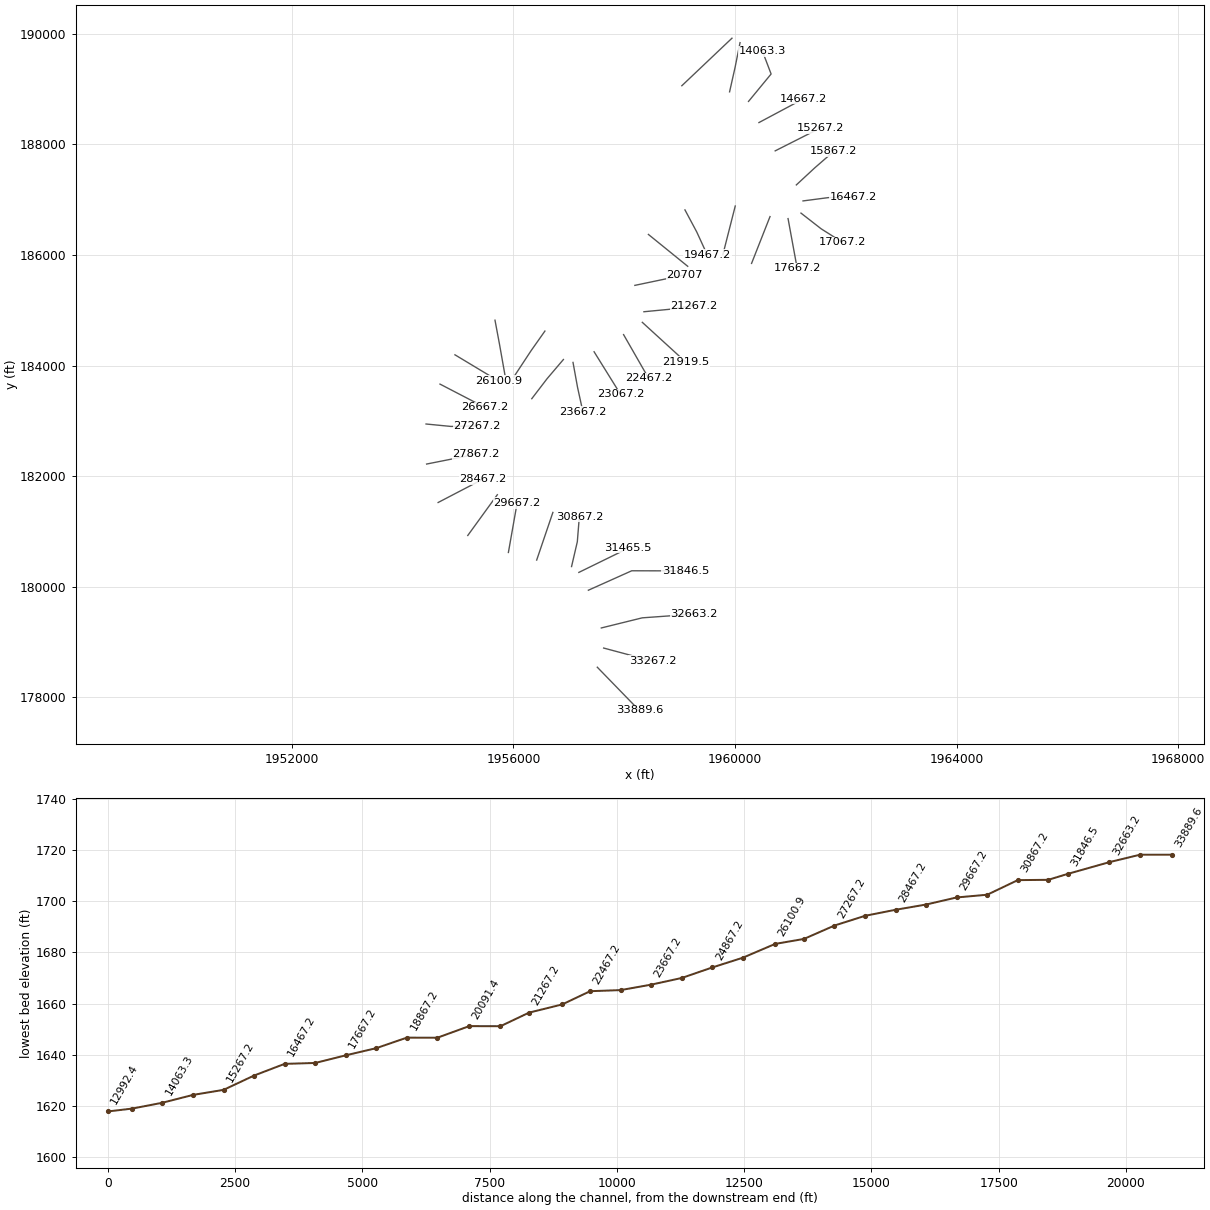
HEC-RAS study BlstnRvr.prj: BlstnRvr

--- BlstnRvr.g01 (geometry) --- (continued)

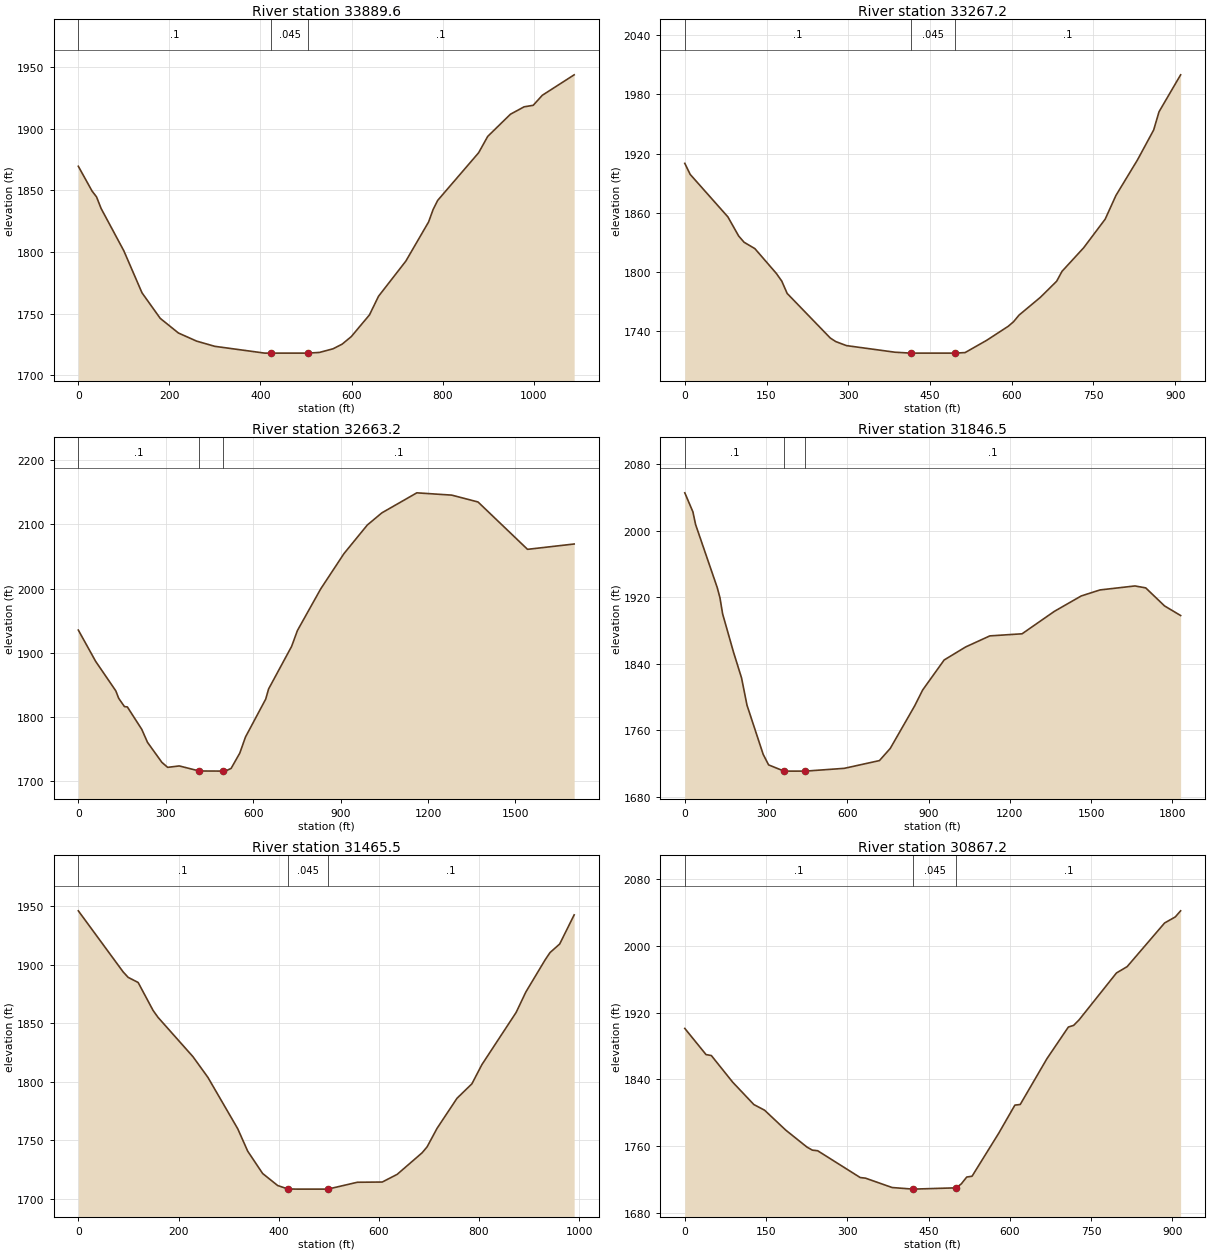
Type RM Length L Ch R = 1 ,33889.6 ,592.5,622.4,652.2
XS GIS Cut Line= 2
     1957513.727      178540.779     1958271.367      177758.871
#Sta/Elev= 30
       0 1869.58      30 1849.58      40 1844.76    49.9 1835.45    99.9 1801.07
   139.8 1767.01   179.8 1746.32   219.8 1734.41   259.7 1727.84   299.7 1723.61
   409.5  1718.1   423.8  1718.1   503.8  1718.1   529.4 1718.66   559.4 1721.62
   579.3 1725.38   599.3 1731.46   639.3 1749.09   659.2  1764.2   719.2 1792.71
   769.1 1824.41   779.1 1834.56   789.1 1841.91     879 1880.53     899 1893.81
   948.9 1911.78   978.9 1917.78   998.9 1919.02  1018.8 1927.12  1088.8 1943.72
#Mann= 3 , 0 , 0
       0      .1       0   423.8    .045       0   503.8      .1       0
Bank Sta=423.8,503.8
XS Rating Curve= 0 ,0
Exp/Cntr=0.3,0.1

Type RM Length L Ch R = 1 ,33267.2 ,576.2,604.1,632
XS GIS Cut Line= 3
      1957628.81      178887.693     1958068.298        178769.9
     1958507.786      178652.108
#Sta/Elev= 30
       0 1910.04     9.9 1898.87    79.1 1855.89    98.9 1836.54   108.8 1830.24
   128.6  1823.8   168.2  1798.6     178 1790.91   187.9 1778.46   267.1 1733.33
     277  1729.8   296.7 1725.71   385.8 1719.02     415  1718.1     495  1718.1
   514.4 1718.64   553.9    1731   593.5 1745.21   603.4 1749.87   613.3 1756.48
   652.8 1774.64   682.5 1790.83   692.4 1800.88     732 1824.62   771.5 1853.58
   791.3 1877.58   830.9  1913.6   860.5 1943.77   870.4 1962.25     910 1999.58
#Mann= 3 , 0 , 0
       0      .1       0     415    .045       0     495      .1       0
Bank Sta=415,495
XS Rating Curve= 0 ,0
Exp/Cntr=0.3,0.1

Type RM Length L Ch R = 1 ,32663.2 ,806.8,816.7,826.5
XS GIS Cut Line= 3
     1957585.974      179251.303      1958325.31      179434.476
      1959262.57      179501.905
#Sta/Elev= 30
       0 1935.18    59.4 1886.45   128.6 1840.41   138.5 1828.77   158.3 1815.83
   168.2 1815.32   217.6 1780.42   237.4 1760.06   286.9 1728.75   306.6 1721.08
   346.2 1723.28     415 1715.39     495 1715.25   504.5 1715.18   524.3 1719.47
     554 1743.28   573.7 1768.52     643 1827.54   652.9 1843.33     732 1909.89
   751.8 1934.48   831.7 1999.42   911.6 2054.53   991.6 2099.07  1041.6 2118.04
  1161.6 2149.28  1281.5 2145.68  1371.5 2135.02  1541.4 2061.14  1701.4 2069.45
#Mann= 3 , 0 , 0
       0      .1       0     415    .045       0     495      .1       0
Bank Sta=415,495
XS Rating Curve= 0 ,0
Exp/Cntr=0.3,0.1

Type RM Length L Ch R = 1 ,31846.5 ,379.2,381,382.9
XS GIS Cut Line= 3
     1957352.446      179934.063     1958135.296      180286.022
     1959107.484      180284.079
#Sta/Elev= 30
       0 2045.35    29.9 2022.52    39.9 2007.19   119.8 1931.34   129.8 1919.14
   139.7 1899.68   179.6 1853.96   209.6 1822.61   229.6 1789.94   289.4 1730.78
   309.4 1718.11   365.5 1710.73   379.3  1710.6   445.5 1710.61   588.8 1713.96
   718.6 1723.28   758.5 1737.91   848.4 1788.95   878.2 1808.21   957.5 1844.29
  1036.9 1859.97  1126.2 1873.27  1245.2 1875.79  1364.3 1902.76  1463.5 1921.29
  1532.9 1928.55  1661.9 1933.34  1701.6 1931.02    1771 1909.35  1830.5 1897.77
#Mann= 3 , 0 , 0
       0      .1       0   365.5    .045       0   445.5      .1       0
Bank Sta=365.5,445.5
XS Rating Curve= 0 ,0
Exp/Cntr=0.3,0.1

Type RM Length L Ch R = 1 ,31465.5 ,549,598.2,655.6
XS GIS Cut Line= 3
     1957180.693      180256.668     1957930.852      180624.595
     1958062.338      180705.509
#Sta/Elev= 30
       0 1945.89    89.5 1893.73    99.5 1889.07   119.4 1884.73   149.2 1860.89
   159.2 1854.89   228.8  1821.4   258.6 1803.78   318.3  1759.8   338.2 1740.66
     368 1721.63   397.9 1711.39   418.1 1708.46   437.7  1708.3   498.1  1708.3
     557 1714.16   606.8 1714.36   636.6 1720.92   686.3  1739.3   696.3 1744.39
   716.2 1760.21     756 1785.85   785.8 1798.24   805.7 1814.59   874.1 1859.17
   893.4 1876.55     932 1904.06   941.7 1910.24     961 1917.57   989.9 1942.43
#Mann= 3 , 0 , 0
       0      .1       0   418.1    .045       0   498.1      .1       0
Bank Sta=418.1,498.1
XS Rating Curve= 0 ,0
Exp/Cntr=0.3,0.1

Type RM Length L Ch R = 1 ,30867.2 ,605.5,600,586.3
XS GIS Cut Line= 3
     1957049.046      180362.264     1957153.046      180811.445
     1957189.342      181263.921
#Sta/Elev= 30
       0    1901    39.2 1869.63      49 1868.47    88.3 1836.57   127.5 1809.62
   147.2 1802.92   186.4 1778.93   225.6 1758.56   235.4 1754.97   245.2 1754.24
   323.7 1722.08   333.5 1721.34   382.6 1710.09   421.1 1708.18   501.1 1709.74
   510.4 1714.59   520.3 1722.69   530.1 1723.66   579.5 1775.44   609.1 1808.96
     619 1809.74   668.3 1864.72   707.8 1902.64   717.6 1904.68   727.5 1911.18
   796.6 1967.56   816.3 1975.13   885.4 2027.51   905.1 2034.78     915 2042.11
#Mann= 3 , 0 , 0
       0      .1       0   421.1    .045       0   501.1      .1       0
Bank Sta=421.1,501.1
XS Rating Curve= 0 ,0
Exp/Cntr=0.3,0.1

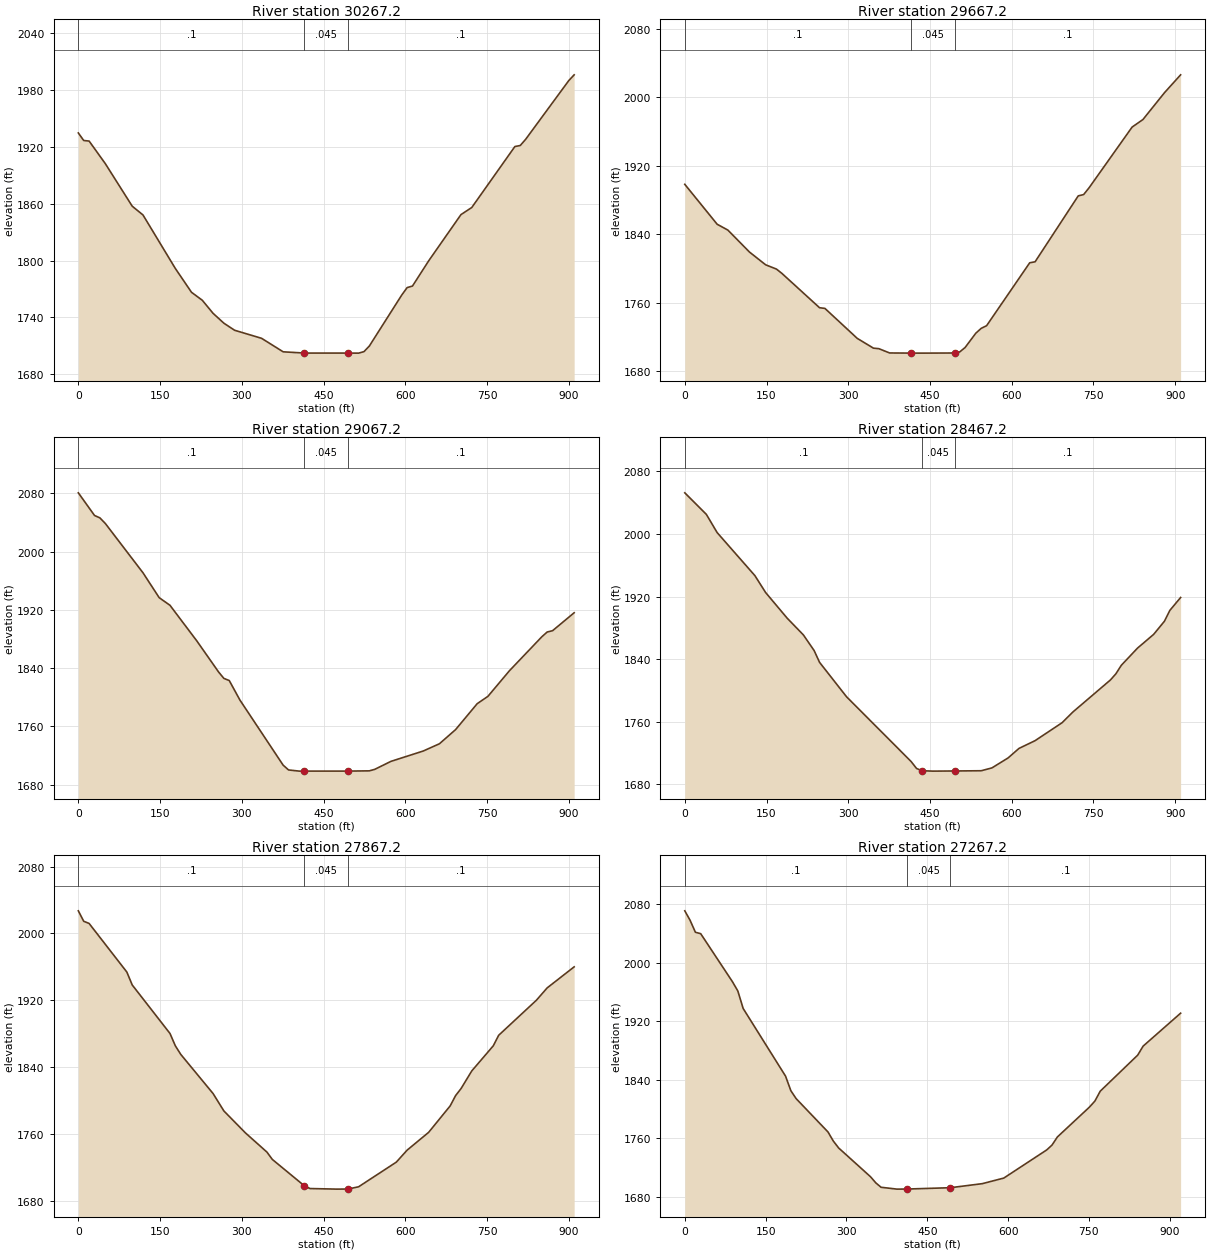
Type RM Length L Ch R = 1 ,30267.2 ,591.6,600,608.4
XS GIS Cut Line= 3
     1956419.386      180479.963     1956565.582      180910.837
     1956711.777       181341.71
#Sta/Elev= 30
       0 1934.34     9.9 1926.39    19.8  1925.8    49.5 1902.05    98.9 1857.23
   118.7 1847.96     178 1791.68   207.7 1766.56   227.5 1758.16   247.3  1744.4
   267.1 1734.02   286.8 1726.56   336.3 1718.09   375.9 1703.87     415 1702.54
     495 1702.52   514.4 1702.48   524.2 1704.03   534.1 1709.95   593.5 1763.59
   603.4 1771.47   613.3 1773.14   642.9 1799.59   702.3 1848.38   722.1 1855.84
   801.2 1920.02   811.1 1921.14     821 1927.67   900.1 1989.47     910 1995.56
#Mann= 3 , 0 , 0
       0      .1       0     415    .045       0     495      .1       0
Bank Sta=415,495
XS Rating Curve= 0 ,0
Exp/Cntr=0.3,0.1

Type RM Length L Ch R = 1 ,29667.2 ,625,600,575
XS GIS Cut Line= 3
     1955908.619      180617.216     1955987.583      181065.311
     1956066.547      181513.407
#Sta/Elev= 30
       0 1898.33    59.4 1851.76    79.1 1844.93   118.7 1819.34   148.4 1804.45
   168.2 1799.46     178 1794.55   247.3 1754.38   257.2 1753.58   316.5 1718.63
   346.2 1707.24   356.1 1706.62   375.9  1701.6     415 1701.46   435.2 1701.42
     495 1701.57   504.5  1702.8   514.4 1707.94   534.1 1724.66     544 1730.32
   553.9 1733.41     633 1806.78   642.9 1807.97   722.1 1884.86     732 1886.38
   741.8 1894.13     821 1965.13   840.8 1973.88   880.3 2005.15     910 2026.06
#Mann= 3 , 0 , 0
       0      .1       0     415    .045       0     495      .1       0
Bank Sta=415,495
XS Rating Curve= 0 ,0
Exp/Cntr=0.3,0.1

Type RM Length L Ch R = 1 ,29067.2 ,625.6,600,574.4
XS GIS Cut Line= 3
      1955175.41      180924.924     1955442.075       181293.59
     1955708.741      181662.256
#Sta/Elev= 30
       0 2080.73    29.7 2049.66    39.6 2046.32    49.5 2038.68   118.7 1970.93
   148.4 1936.79   168.2 1926.34   217.6  1877.3   257.2 1835.01   267.1 1825.98
     277 1822.99   296.7  1796.1   375.9 1706.87   385.8 1700.28   405.5 1698.66
     415  1698.7     495  1698.7   534.1 1699.04     544 1701.09   573.7 1712.04
     633 1726.26   662.7 1736.21   692.4 1755.67     732 1791.22   751.7 1801.29
   791.3 1836.54   850.6 1883.05   860.5 1889.64   870.4 1891.46     910 1916.08
#Mann= 3 , 0 , 0
       0      .1       0     415    .045       0     495      .1       0
Bank Sta=415,495
XS Rating Curve= 0 ,0
Exp/Cntr=0.3,0.1

Type RM Length L Ch R = 1 ,28467.2 ,615.7,600,584.3
XS GIS Cut Line= 3
     1954640.094       181521.53     1955043.409      181732.153
     1955446.724      181942.776
#Sta/Elev= 30
       0 2052.63    39.6 2025.04    59.4 2001.73   128.6 1946.76   148.4 1925.02
   187.9 1892.28   217.6 1870.89   237.4 1850.82   247.3 1835.82   296.7 1791.87
   415.4 1708.88   425.3 1700.04   435.2 1697.12     455 1696.61     495  1696.8
     544  1697.1   563.8 1700.76   593.5 1713.56   613.3 1725.65   642.9 1735.59
   692.4 1758.52   712.2  1772.2   781.4 1813.38   791.3 1821.23   801.2 1832.04
   830.9 1853.98   860.5 1871.55   880.3 1888.38   890.2  1902.2     910 1918.74
#Mann= 3 , 0 , 0
       0      .1       0   435.2    .045       0     495      .1       0
Bank Sta=435.2,495
XS Rating Curve= 0 ,0
Exp/Cntr=0.3,0.1

Type RM Length L Ch R = 1 ,27867.2 ,616.3,600,590.3
XS GIS Cut Line= 3
     1954432.191      182217.412     1954878.438      182306.235
     1955324.682      182395.058
#Sta/Elev= 30
       0 2027.03     9.9 2014.53    19.8 2011.94      89 1953.85    98.9  1938.4
   168.2 1880.39     178  1865.7   187.9 1855.45   247.3 1808.55   267.1 1787.76
   306.6 1761.54   346.2  1738.5   356.1 1729.74     415 1698.11   425.3 1694.94
   474.8 1694.25     495 1694.37   514.4 1697.05   583.6 1726.52   603.4 1740.84
   642.9 1762.13   682.5 1793.82   692.4 1806.09   702.3 1814.37   722.1  1835.6
   761.6 1865.65   771.5 1878.23   840.8 1920.18   860.5  1934.9     910 1960.04
#Mann= 3 , 0 , 0
       0      .1       0     415    .045       0     495      .1       0
Bank Sta=415,495
XS Rating Curve= 0 ,0
Exp/Cntr=0.3,0.1

Type RM Length L Ch R = 1 ,27267.2 ,621.1,600,572.4
XS GIS Cut Line= 3
     1954421.602      182942.095     1954872.289      182897.977
     1955339.417      182907.851
#Sta/Elev= 30
       0 2070.83     9.8 2057.93    19.7 2041.53    29.5 2039.61    88.6 1973.75
    98.4  1961.3   108.3 1937.37     187 1844.84   196.9 1824.86   206.7 1814.09
   265.8 1768.52   275.6 1756.17   285.5 1746.71   344.6 1707.42   354.4 1699.05
   364.2    1693   393.8 1690.46   412.8 1690.58   492.8 1692.39   552.2 1697.95
     592 1705.58   671.6 1744.02   681.5 1750.73   691.4 1761.75   751.1  1802.7
     761 1810.84     771 1824.38   840.5 1873.63   850.5  1885.9   920.1 1930.94
#Mann= 3 , 0 , 0
       0      .1       0   412.8    .045       0   492.8      .1       0
Bank Sta=412.8,492.8
XS Rating Curve= 0 ,0
Exp/Cntr=0.3,0.1

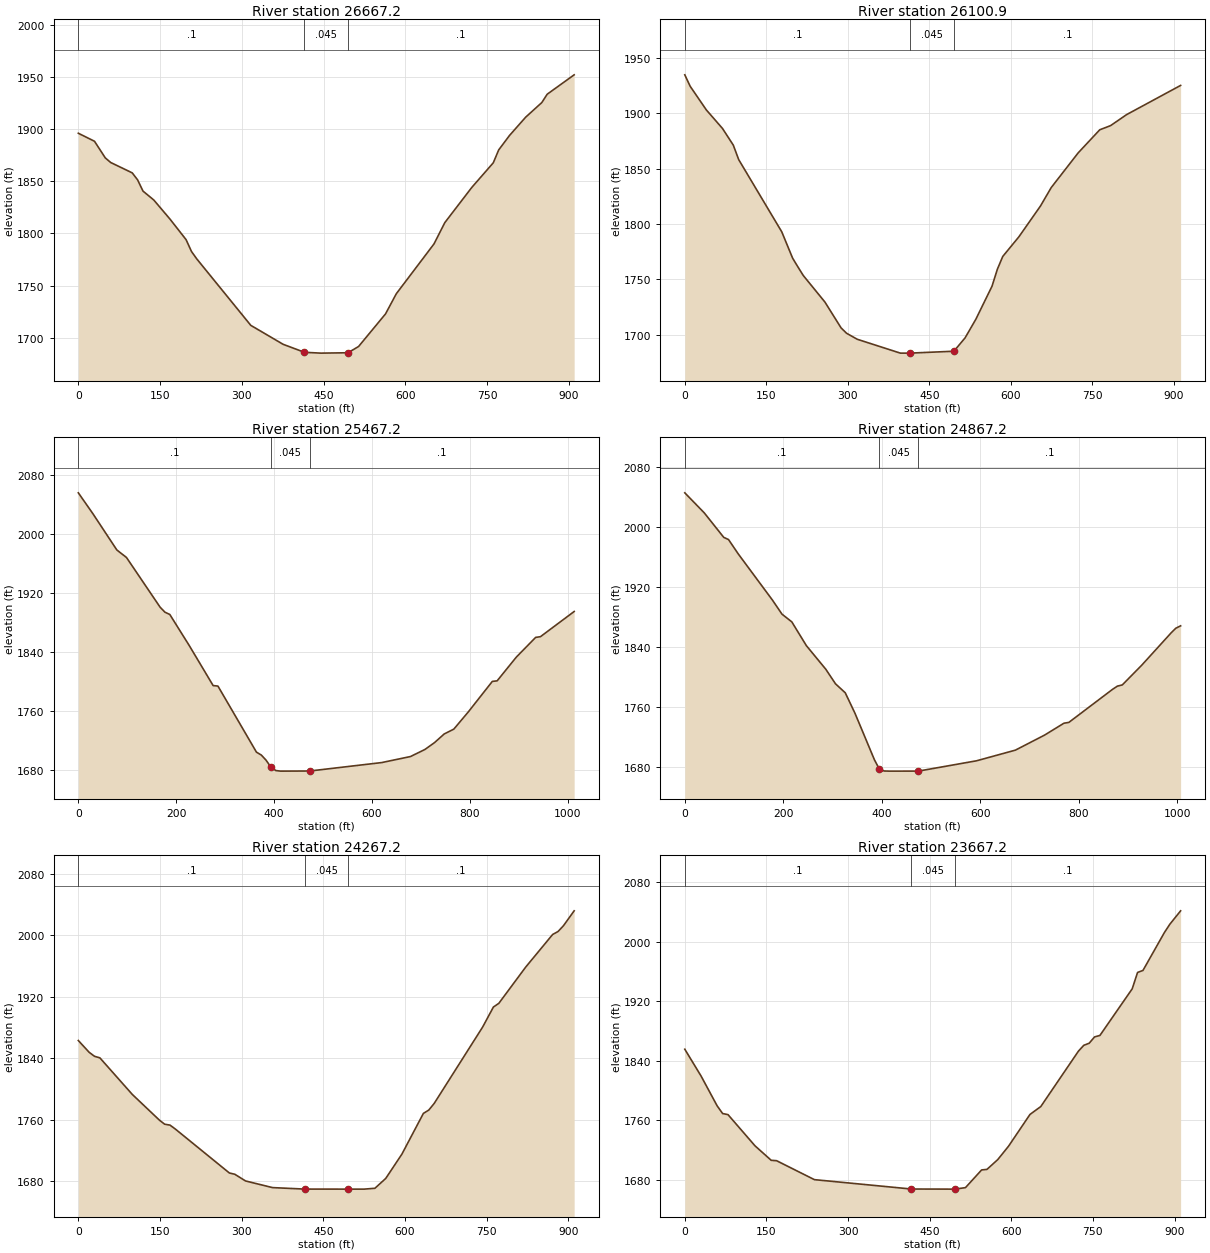
Type RM Length L Ch R = 1 ,26667.2 ,569.8,566.3,562.9
XS GIS Cut Line= 3
     1954673.916      183664.025     1955077.604      183454.118
     1955481.291       183244.21
#Sta/Elev= 30
       0 1896.12    29.7 1888.42    49.5 1872.47    59.4 1868.06    98.9 1858.12
   108.8  1851.4   118.7 1840.63   138.5 1832.09   168.2  1813.8   197.8 1794.04
   207.7 1782.69   217.6 1775.46   316.5 1711.88   375.9 1693.68     415 1686.02
   445.1 1685.23     495 1685.58   514.4 1691.62   563.8 1722.85   583.6  1742.2
   652.8 1789.99   672.6 1810.39   722.1 1844.13   761.6  1867.8   771.5 1880.12
   791.3 1893.95     821 1911.52   850.6 1925.53   860.5 1933.54     910 1952.15
#Mann= 3 , 0 , 0
       0      .1       0     415    .045       0     495      .1       0
Bank Sta=415,495
XS Rating Curve= 0 ,0
Exp/Cntr=0.3,0.1

Type RM Length L Ch R = 1 ,26100.9 ,681.9,633.7,584.9
XS GIS Cut Line= 2
     1954943.847      184194.284     1955725.283      183723.121
#Sta/Elev= 30
       0 1934.84     9.9 1924.48    39.7 1903.09    69.4 1886.34    89.3 1871.26
    99.2  1858.2   178.5 1792.88   198.4 1769.16   208.3 1761.11   218.2 1753.36
   257.9 1729.44   287.6 1706.12   297.6 1701.28   317.4  1695.8   396.7 1683.28
   415.2  1683.3   495.2    1685   515.8 1697.04   535.6 1713.86   565.4 1743.76
   575.3 1759.19   585.2 1770.69   614.9 1788.45   654.6 1816.28   674.4 1832.96
     724 1864.31   763.7 1885.17   783.6 1888.92   813.3 1898.93   912.5 1925.27
#Mann= 3 , 0 , 0
       0      .1       0   415.2    .045       0   495.2      .1       0
Bank Sta=415.2,495.2
XS Rating Curve= 0 ,0
Exp/Cntr=0.3,0.1

Type RM Length L Ch R = 1 ,25467.2 ,644.1,600,558.1
XS GIS Cut Line= 3
     1955666.766      184820.597     1955746.314      184395.074
     1955847.505      183823.701
#Sta/Elev= 30
       0 2056.16    29.5 2028.06    78.7  1978.5    98.4 1968.27   167.2 1900.64
   177.1 1893.89   186.9 1890.83   226.3 1848.98   275.5 1794.18   285.3 1793.49
     364 1703.69   373.9 1699.75   383.7 1692.75   392.9 1683.91   403.4 1678.71
   413.2  1677.9   472.9 1678.06   619.8 1689.52   678.8 1697.73   708.3 1707.35
   727.9 1716.67   747.6 1728.38   767.3    1735   796.8  1758.3     846 1799.87
   855.8  1800.6   895.1 1832.92   934.5 1859.66   944.3 1860.62  1013.2 1894.85
#Mann= 3 , 0 , 0
       0      .1       0   392.9    .045       0   472.9      .1       0
Bank Sta=392.9,472.9
XS Rating Curve= 0 ,0
Exp/Cntr=0.3,0.1

Type RM Length L Ch R = 1 ,24867.2 ,605.3,600,595.8
XS GIS Cut Line= 3
     1956567.798       184623.67     1956318.088      184268.311
     1956003.825      183790.158
#Sta/Elev= 30
       0 2045.02    39.5 2018.32      79 1985.71    88.8  1982.7   108.6 1963.53
   177.7 1902.26   197.4 1883.24   217.2 1873.07   246.8 1841.33   286.3 1809.83
     306 1790.42   325.7 1778.53   345.5 1751.17     385 1689.15   394.3 1677.54
   404.7 1674.28   414.6  1674.1   474.3 1674.14   592.2 1687.87   671.1 1702.07
   730.3 1722.11   769.7 1737.97   779.6 1739.04   868.4 1783.15   878.2  1787.4
   888.1 1788.99   927.6 1815.32   986.8 1858.07   996.6 1864.49  1006.5 1867.76
#Mann= 3 , 0 , 0
       0      .1       0   394.3    .045       0   474.3      .1       0
Bank Sta=394.3,474.3
XS Rating Curve= 0 ,0
Exp/Cntr=0.3,0.1

Type RM Length L Ch R = 1 ,24267.2 ,551.2,600,647.9
XS GIS Cut Line= 3
     1956901.901      184109.213     1956606.995      183761.746
     1956331.038      183400.148
#Sta/Elev= 30
       0 1863.28    19.8 1848.01    29.7 1842.76    39.6 1840.72    99.1 1793.18
   148.6 1759.93   158.5 1754.44   168.4 1753.24   178.3 1748.06   277.4 1690.97
   287.3 1689.34   307.1 1680.62   356.7 1671.97   415.7 1670.04   495.7    1670
     525 1669.99   544.7  1671.1   564.5 1683.84   594.2 1715.44   633.7 1768.48
   643.6 1772.81   653.5  1781.4   742.5 1880.76   762.3 1906.84   772.2 1911.59
   821.6 1958.78   871.1 2001.22     881 2005.05   890.8 2012.46   910.6 2031.97
#Mann= 3 , 0 , 0
       0      .1       0   415.7    .045       0   495.7      .1       0
Bank Sta=415.7,495.7
XS Rating Curve= 0 ,0
Exp/Cntr=0.3,0.1

Type RM Length L Ch R = 1 ,23667.2 ,579.3,600,618.8
XS GIS Cut Line= 3
      1957075.37      184056.421     1957156.804      183607.249
     1957253.782      183163.014
#Sta/Elev= 30
       0 1855.33    29.8 1819.45    59.5  1779.2    69.5 1768.95    79.4 1767.46
     129 1725.59   158.8  1706.1   168.7 1705.57   238.2 1680.12   416.5 1667.52
     496 1667.39   496.5 1667.39   515.8  1669.4   545.5 1693.17   555.3 1693.91
   575.1 1707.02   594.9 1724.99   634.4 1767.76   654.2 1778.29   723.4 1852.73
   733.3 1860.63   743.2  1863.4     753 1871.85   762.9 1873.86   822.2 1936.43
   832.1  1958.5     842 1961.17   881.5 2012.22   891.4 2023.26   911.2 2041.25
#Mann= 3 , 0 , 0
       0      .1       0   416.5    .045       0   496.5      .1       0
Bank Sta=416.5,496.5
XS Rating Curve= 0 ,0
Exp/Cntr=0.3,0.1

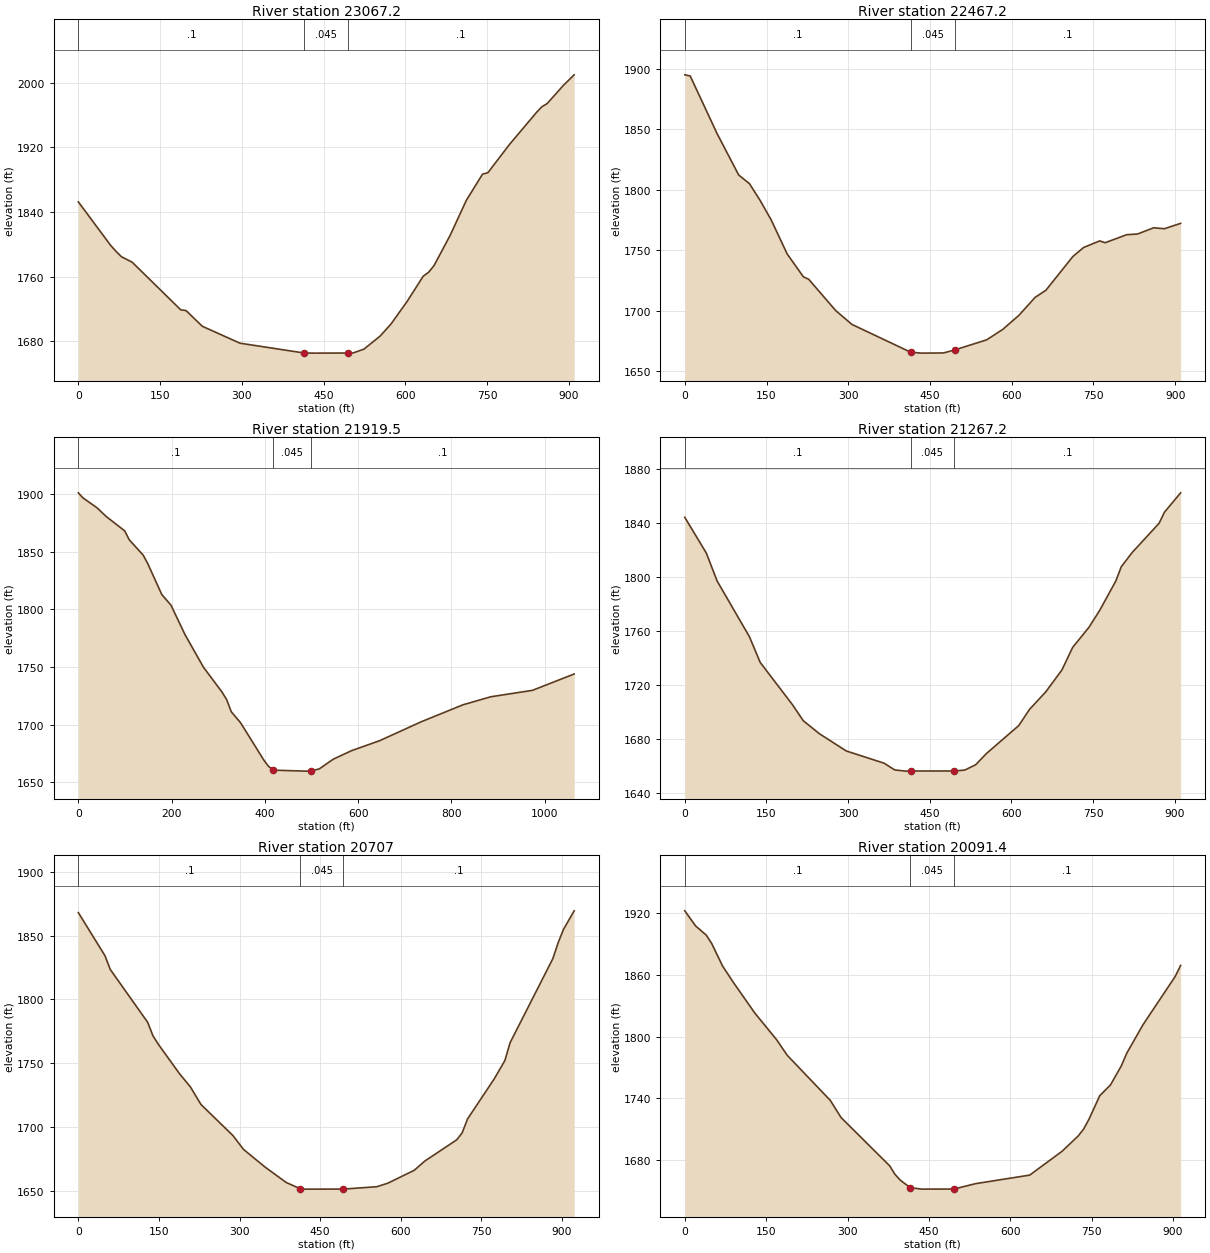
Type RM Length L Ch R = 1 ,23067.2 ,602,600,598
XS GIS Cut Line= 3
      1957455.75      184249.259     1957695.623      183862.626
     1957935.497      183475.992
#Sta/Elev= 30
       0 1852.44    59.4 1798.53    69.2 1791.18    79.1 1784.55    98.9 1777.73
   187.9 1718.87   197.8 1717.87   227.5  1698.5   296.7 1677.55     415 1665.36
   435.2 1665.26     495  1665.4   504.5 1665.51   524.2  1670.2   553.9 1686.36
   573.7 1701.16   603.4 1729.19     633 1760.46   642.9 1765.33   652.8 1773.52
   682.5 1811.12   712.2 1854.41   741.8 1886.66   751.7 1888.52   791.3 1923.46
   840.8 1963.02   850.6 1970.03   860.5 1974.07   890.2 1996.52     910  2009.6
#Mann= 3 , 0 , 0
       0      .1       0     415    .045       0     495      .1       0
Bank Sta=415,495
XS Rating Curve= 0 ,0
Exp/Cntr=0.3,0.1

Type RM Length L Ch R = 1 ,22467.2 ,530.7,547.8,564.9
XS GIS Cut Line= 3
     1957988.176      184559.586     1958214.042      184164.605
     1958439.909      183769.625
#Sta/Elev= 30
       0 1895.03     9.9  1894.1    59.4  1846.3    98.9 1812.19   118.7    1805
   138.5 1790.96   158.3 1775.25   187.9 1746.87   217.6 1727.98   227.5 1725.89
     277 1700.02   306.6 1688.61     415  1665.5   435.2 1664.83   474.8 1664.98
     495 1667.41   553.9  1675.8   583.6 1684.47   613.3 1696.13   642.9 1710.93
   662.7 1716.81   712.2 1744.75     732 1752.22   761.6 1757.68   771.5 1756.16
   811.1  1762.8   830.9 1763.34   860.5  1768.5   880.3 1767.75     910 1772.17
#Mann= 3 , 0 , 0
       0      .1       0     415    .045       0     495      .1       0
Bank Sta=415,495
XS Rating Curve= 0 ,0
Exp/Cntr=0.3,0.1

Type RM Length L Ch R = 1 ,21919.5 ,604.8,652.2,702.7
XS GIS Cut Line= 2
     1958326.396      184781.571     1959110.856      184063.464
#Sta/Elev= 30
       0 1901.09     9.9 1896.72    39.8  1888.2    59.6 1880.62    99.4  1868.1
   109.3  1860.3   139.2 1847.01   149.1 1839.52   178.9 1812.96   198.8 1803.61
   228.6 1778.26   268.4  1749.8   308.1  1728.3   318.1 1721.74     328 1711.21
   347.9 1701.72   397.6 1669.42   407.5 1664.02     418 1660.52     487 1659.67
     498 1659.73   516.8 1661.59   546.7 1670.01   586.4 1677.48   646.1 1686.04
   735.5 1702.49     825 1717.21   884.6 1724.17   974.1 1729.75  1063.5 1743.93
#Mann= 3 , 0 , 0
       0      .1       0     418    .045       0     498      .1       0
Bank Sta=418,498
XS Rating Curve= 0 ,0
Exp/Cntr=0.3,0.1

Type RM Length L Ch R = 1 ,21267.2 ,554.1,560.2,563.3
XS GIS Cut Line= 3
     1958355.547      184973.568     1958808.319      185016.984
     1959258.974       185085.64
#Sta/Elev= 30
       0 1844.25    39.6 1817.77    59.3  1797.2   118.7 1755.92   138.4 1736.97
   197.8 1705.59   217.5 1693.81   247.2 1684.15   296.6 1671.37   365.9 1662.36
   385.6 1657.35   405.4 1656.46   414.8 1656.55   494.8 1656.56   514.3 1657.24
   534.1 1661.14     554 1669.47   613.4 1690.17   633.2 1702.15     663 1715.12
   692.7 1731.33   712.5  1748.1   742.2 1762.81   762.1 1775.44   791.8 1797.23
   801.7  1807.7   821.5 1818.13   871.1 1839.84     881 1848.06   910.7 1862.39
#Mann= 3 , 0 , 0
       0      .1       0   414.8    .045       0   494.8      .1       0
Bank Sta=414.8,494.8
XS Rating Curve= 0 ,0
Exp/Cntr=0.3,0.1

Type RM Length L Ch R = 1 ,20707   ,665,615.6,566.3
XS GIS Cut Line= 2
     1958191.622       185450.79     1959094.519      185640.268
#Sta/Elev= 30
       0 1868.07    49.6 1834.24    59.5 1823.42     129 1782.05   138.9 1771.42
   148.8 1764.84   188.5 1741.56   208.3  1731.5   228.2 1717.56   287.7 1693.19
   307.5 1682.28   347.2 1668.56   386.9 1656.35   413.3 1651.42   416.6 1651.17
   493.3 1651.19   555.5 1653.08   575.4 1655.74     625 1665.93   644.8 1673.21
   704.3 1689.91   714.2 1695.33   724.2 1706.19   773.8 1737.59   793.6 1751.93
   803.5  1766.1   882.9 1831.92   892.8 1844.41   902.7 1854.84   922.6 1869.46
#Mann= 3 , 0 , 0
       0      .1       0   413.3    .045       0   493.3      .1       0
Bank Sta=413.3,493.3
XS Rating Curve= 0 ,0
Exp/Cntr=0.3,0.1

Type RM Length L Ch R = 1 ,20091.4 ,646.5,624.1,598.4
XS GIS Cut Line= 2
     1958436.389      186372.477     1959145.853      185796.103
#Sta/Elev= 30
       0 1922.53    19.9 1907.83    39.7 1898.78    49.7 1890.59    69.6 1868.75
    89.4 1852.86   129.2  1822.8   168.9 1797.12   188.8 1781.71   268.3 1737.68
   288.1 1720.96   377.6 1673.99   387.5 1665.61   397.4 1659.86   415.9 1652.54
   437.2 1651.19   495.9 1651.28   536.5 1656.57   635.9 1664.86   695.5 1688.08
   725.3 1703.02   735.2  1709.7   745.2 1719.36     765 1742.27   784.9 1752.84
   804.8 1771.38   814.7 1783.62   844.5 1811.28   904.2  1858.6   914.1 1869.29
#Mann= 3 , 0 , 0
       0      .1       0   415.9    .045       0   495.9      .1       0
Bank Sta=415.9,495.9
XS Rating Curve= 0 ,0
Exp/Cntr=0.3,0.1

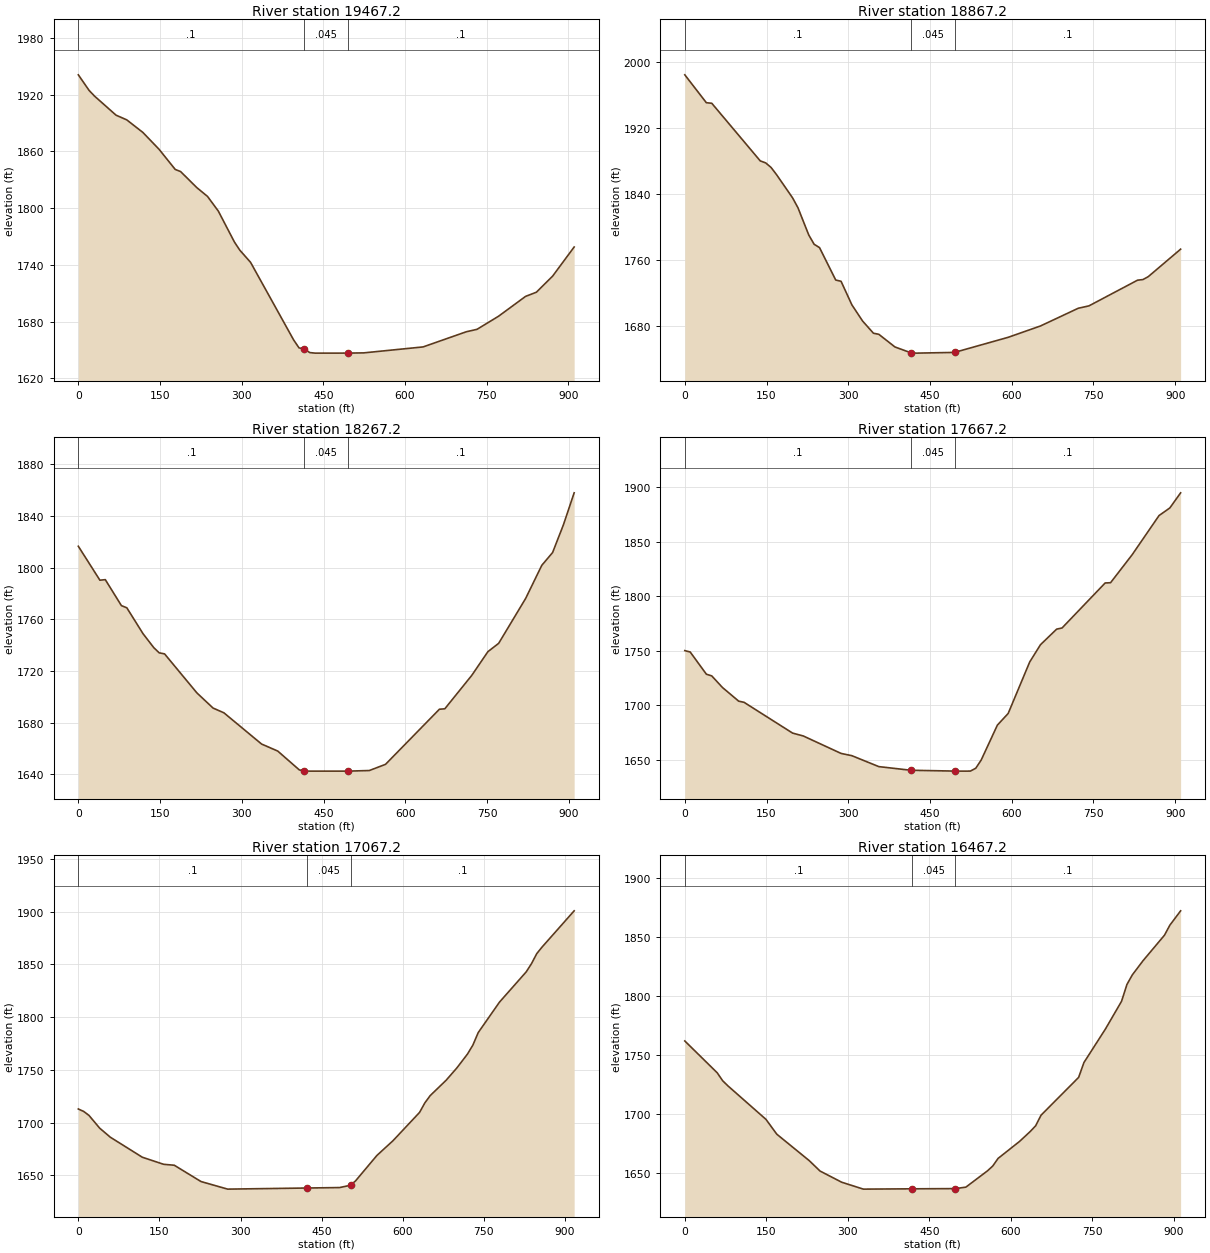
Type RM Length L Ch R = 1 ,19467.2 ,641.1,600,562.3
XS GIS Cut Line= 3
      1959096.31      186816.523     1959310.187      186415.127
      1959499.89      186000.441
#Sta/Elev= 30
       0 1941.06    19.8 1924.57    29.7 1918.59    69.2 1898.42      89 1893.41
   118.6  1880.1   148.3  1862.3     178 1840.98   187.9 1838.72   217.5 1821.83
   237.3 1812.44   257.1 1796.99   286.7 1764.24   296.6 1755.61   316.4  1742.7
   395.5 1660.63   405.4 1652.23   414.8 1651.08   425.2 1647.25     435 1646.67
   494.8  1646.7   524.2 1646.93   633.3 1653.23   712.6 1669.25   732.4 1671.85
     772 1685.73   821.6  1706.7   841.4  1711.1   871.2 1728.09   910.8 1758.94
#Mann= 3 , 0 , 0
       0      .1       0   414.8    .045       0   494.8      .1       0
Bank Sta=414.8,494.8
XS Rating Curve= 0 ,0
Exp/Cntr=0.3,0.1

Type RM Length L Ch R = 1 ,18867.2 ,606.9,600,593.1
XS GIS Cut Line= 3
     1960004.205      186886.613     1959892.208      186445.612
     1959780.211      186004.611
#Sta/Elev= 30
       0 1984.92    39.6    1951    49.5 1950.37   138.5  1880.3   148.4  1877.9
   158.3 1872.36   168.2  1863.8   197.8 1835.43   207.7 1823.37   227.5 1790.29
   237.4 1778.99   247.3 1774.91     277 1735.54   286.8    1734   306.6 1705.44
   326.4 1685.63   346.2  1670.9   356.1 1669.58   385.8 1654.15     415 1647.11
   425.3  1646.7     495 1647.57   593.5 1665.92   652.8  1679.7   722.1 1701.22
   741.8 1704.14   830.9 1735.34   840.8 1736.08   850.6 1739.64     910 1773.04
#Mann= 3 , 0 , 0
       0      .1       0     415    .045       0     495      .1       0
Bank Sta=415,495
XS Rating Curve= 0 ,0
Exp/Cntr=0.3,0.1

Type RM Length L Ch R = 1 ,18267.2 ,569.1,600,630.9
XS GIS Cut Line= 3
     1960631.803      186695.313     1960465.349      186271.854
     1960298.894      185848.394
#Sta/Elev= 30
       0 1816.54    39.6 1790.28    49.5  1790.7    79.1  1770.6      89 1768.94
   118.7 1748.93   138.5  1738.1   148.4  1734.1   158.3 1733.28   217.6 1703.11
   247.3 1691.38   267.1 1687.73   336.3 1663.56     366 1658.11   405.5 1643.57
     415 1642.66   425.3  1642.6     495  1642.6   534.1 1643.06   563.8 1647.85
   662.7 1690.47   672.6  1690.8   722.1 1716.67   751.7    1735   771.5 1741.46
     821 1776.18   850.6 1801.78   870.4 1811.65   890.2 1833.01     910 1857.86
#Mann= 3 , 0 , 0
       0      .1       0     415    .045       0     495      .1       0
Bank Sta=415,495
XS Rating Curve= 0 ,0
Exp/Cntr=0.3,0.1

Type RM Length L Ch R = 1 ,17667.2 ,559.3,600,646.1
XS GIS Cut Line= 3
      1960957.63      186658.794     1961039.537      186211.227
     1961121.444       185763.66
#Sta/Elev= 30
       0 1750.16     9.9  1748.9    39.6 1728.57    49.5 1726.99    69.2 1716.35
    98.9 1703.89   108.8  1702.8   197.8 1674.64   217.6 1671.97   286.8 1656.01
   306.6 1653.95   356.1 1643.93     415 1640.59     495 1639.84   514.4  1639.8
   524.2 1639.84   534.1 1642.48     544 1649.98   573.7 1681.94   593.5  1692.6
     633 1739.73   652.8 1755.58   682.5 1769.83   692.4  1770.9   771.5  1812.1
   781.4 1812.34     821 1837.94   870.4 1873.85   890.2 1880.81     910 1894.66
#Mann= 3 , 0 , 0
       0      .1       0     415    .045       0     495      .1       0
Bank Sta=415,495
XS Rating Curve= 0 ,0
Exp/Cntr=0.3,0.1

Type RM Length L Ch R = 1 ,17067.2 ,555.9,600,633
XS GIS Cut Line= 3
     1961190.988      186758.437     1961556.447      186473.334
     1961939.664      186230.837
#Sta/Elev= 30
       0 1712.81     9.9 1710.51    19.7 1706.73    39.4 1694.69    59.2 1686.05
   118.3 1667.08   157.8 1660.36   177.5 1659.47   226.8 1644.03   276.1 1636.82
   423.5 1637.88   483.2  1638.3   503.5 1640.51   512.8  1644.7   552.2 1668.76
   581.8 1682.66   631.1 1709.58     641 1718.71   650.8 1725.53   680.4 1740.17
   700.1 1751.78   719.8 1764.98   729.7 1773.43   739.6  1785.3     779 1814.23
   828.3 1842.84   838.1 1850.67     848 1860.28   857.9 1866.54     917 1900.76
#Mann= 3 , 0 , 0
       0      .1       0   423.5    .045       0   503.5      .1       0
Bank Sta=423.5,503.5
XS Rating Curve= 0 ,0
Exp/Cntr=0.3,0.1

Type RM Length L Ch R = 1 ,16467.2 ,565.8,600,638.2
XS GIS Cut Line= 3
     1961227.983       186978.95     1961682.107      187038.394
     1962136.422      187050.304
#Sta/Elev= 30
       0 1762.07    59.7 1735.06    69.7 1728.34    79.6 1723.91   149.4  1695.6
   169.3 1683.04     229 1660.63   248.9  1651.8   288.7 1642.33   328.6 1636.47
     418 1636.73     498 1636.91   517.3 1638.16   556.8 1651.88   566.7 1656.03
   576.6 1662.52   616.1 1676.92   635.8 1685.35   645.7 1690.17   655.6 1699.13
   724.8 1731.18   734.6 1743.81   774.2 1772.25   803.8 1795.72   813.7 1809.96
   823.6 1818.06   843.3 1830.09   882.8 1851.73   892.7 1860.22   912.5 1872.38
#Mann= 3 , 0 , 0
       0      .1       0     418    .045       0     498      .1       0
Bank Sta=418,498
XS Rating Curve= 0 ,0
Exp/Cntr=0.3,0.1

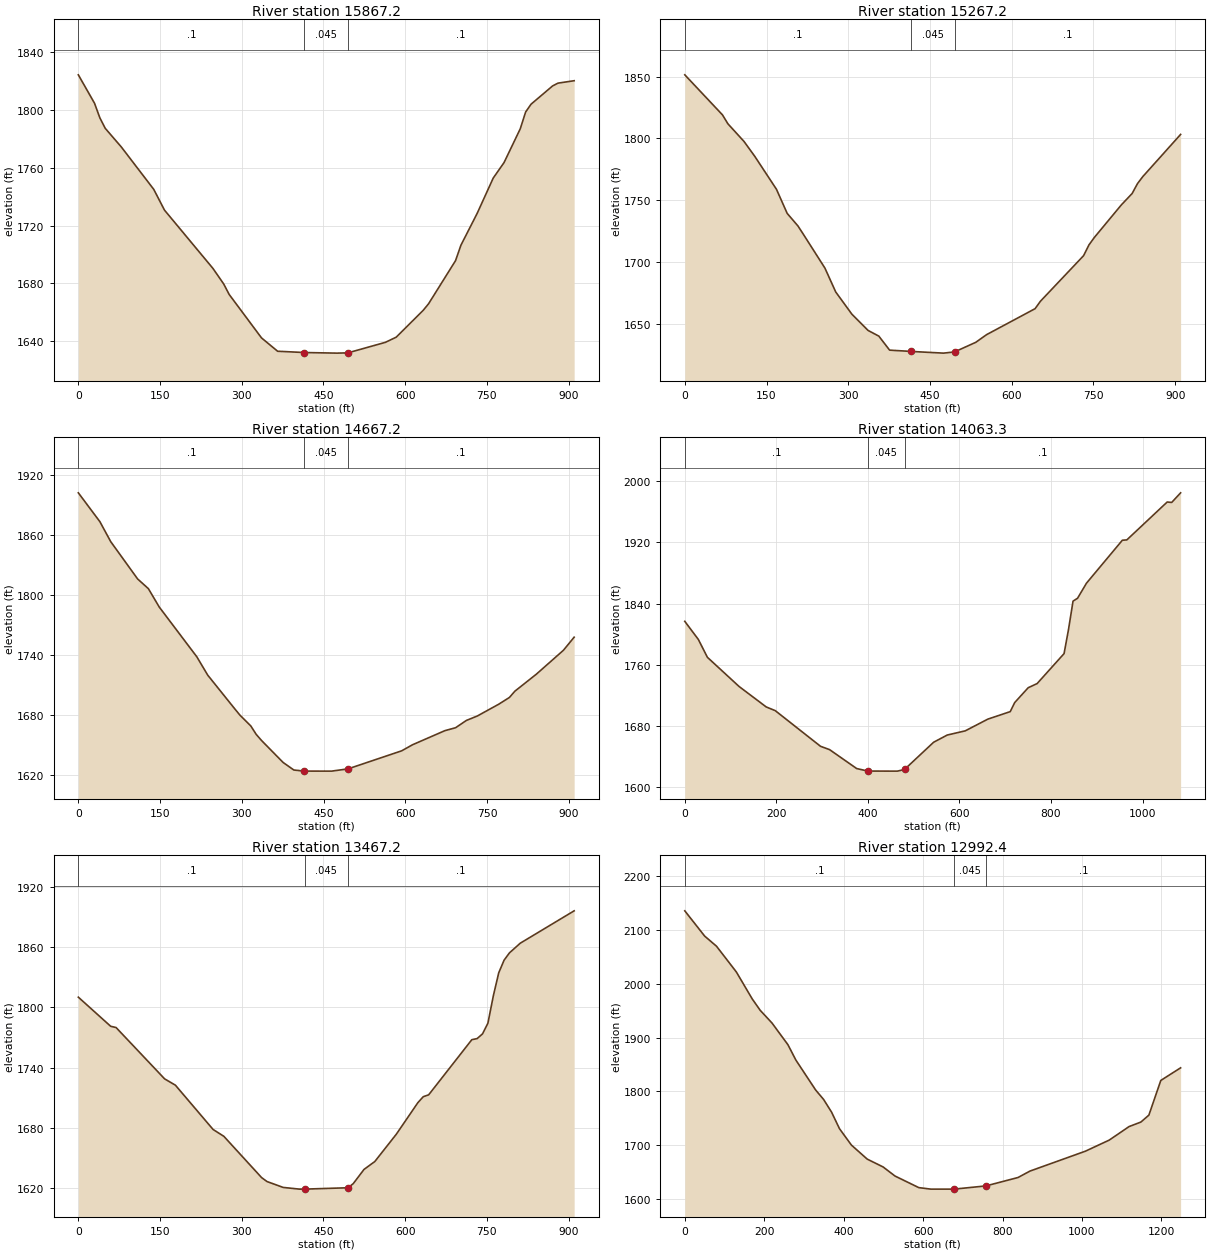
Type RM Length L Ch R = 1 ,15867.2 ,615.4,600,586.4
XS GIS Cut Line= 3
     1961107.223      187268.442     1961440.451      187578.164
     1961783.954      187877.123
#Sta/Elev= 30
       0 1824.07    29.7 1804.46    39.6  1794.3    49.4 1787.13    79.1 1774.17
   138.5 1744.97   158.2 1730.64   247.2 1690.37     267  1679.6   276.9 1672.45
   336.3 1642.42   365.9 1633.21   414.9 1632.32   474.7 1631.91   494.9 1632.09
   563.8 1639.37   583.6 1642.93   633.1 1661.43     643 1665.98   692.5 1695.74
   702.4 1706.42   732.1  1728.3   761.8 1752.84   781.6 1763.49   811.3 1786.76
   821.2 1798.38   831.1 1803.77   870.7  1816.4   880.6 1818.33   910.3    1820
#Mann= 3 , 0 , 0
       0      .1       0   414.9    .045       0   494.9      .1       0
Bank Sta=414.9,494.9
XS Rating Curve= 0 ,0
Exp/Cntr=0.3,0.1

Type RM Length L Ch R = 1 ,15267.2 ,598.8,600,601.2
XS GIS Cut Line= 3
     1960725.501       187884.93     1961131.316      188090.695
     1961537.131       188296.46
#Sta/Elev= 30
       0 1851.49    69.2 1819.06    79.1 1811.88   108.8 1797.52   128.6 1785.43
   168.2 1758.91   187.9 1739.39   207.7 1729.21   217.6 1722.48   257.2 1695.11
     277  1675.8   306.6 1657.86   336.3  1644.7   356.1 1640.08   375.9 1628.74
     415  1627.7   474.8 1626.32     495 1627.28   534.1 1635.08   553.9 1641.28
   642.9 1662.28   652.8 1668.34     732 1705.22   741.8  1713.9   751.7 1719.92
   801.2 1746.25     821 1755.46   830.9 1763.52   840.8 1769.25     910 1803.28
#Mann= 3 , 0 , 0
       0      .1       0     415    .045       0     495      .1       0
Bank Sta=415,495
XS Rating Curve= 0 ,0
Exp/Cntr=0.3,0.1

Type RM Length L Ch R = 1 ,14667.2 ,581.9,603.9,625.9
XS GIS Cut Line= 3
     1960431.949      188396.753      1960833.21      188611.264
      1961234.47      188825.775
#Sta/Elev= 30
       0 1901.74    39.6 1872.97    59.4 1853.13   108.8 1815.92   128.6  1806.2
   148.4 1787.99   217.6 1738.21   237.4 1720.09   286.8 1686.64   296.7 1680.09
   316.5 1669.42   326.4 1661.01   336.3 1654.85   375.9 1632.96   395.6 1625.44
     415 1624.38   464.9 1624.35     495  1626.6   593.5  1644.6   613.3 1650.61
   672.6 1664.66   692.4 1667.61   712.2 1674.88     732 1679.22   771.5 1691.02
   791.3 1697.82   801.2 1704.02   840.8 1721.06   890.2 1744.75     910 1757.85
#Mann= 3 , 0 , 0
       0      .1       0     415    .045       0     495      .1       0
Bank Sta=415,495
XS Rating Curve= 0 ,0
Exp/Cntr=0.3,0.1

Type RM Length L Ch R = 1 ,14063.3 ,570.1,596.1,623.3
XS GIS Cut Line= 3
     1960243.786      188779.388     1960651.604       189275.71
     1960495.195      189687.785
#Sta/Elev= 30
       0 1816.99    29.6 1793.32    49.4 1769.98   118.6 1731.85   177.9 1705.12
   197.6  1700.3   296.5 1653.71   316.2 1649.39   375.5 1624.64     400 1621.35
   464.5 1621.28     480 1623.48   543.6 1659.04   573.2  1668.4   612.7 1673.91
     662 1689.22   710.9 1699.02   720.7 1710.89   750.1 1730.23   769.7  1735.7
   828.5 1774.82   838.3  1806.7   848.1  1843.4   857.9  1847.1   877.4 1866.78
   955.8 1922.94   965.6 1923.38  1053.8 1972.89  1063.6  1972.3  1083.1 1984.88
#Mann= 3 , 0 , 0
       0      .1       0     400    .045       0     480      .1       0
Bank Sta=400,480
XS Rating Curve= 0 ,0
Exp/Cntr=0.3,0.1

Type RM Length L Ch R = 1 ,13467.2 ,507.6,474.8,440.8
XS GIS Cut Line= 3
     1959901.826      188952.702     1960001.463      189396.965
     1960090.677      189843.106
#Sta/Elev= 30
       0 1810.08    59.4 1781.09    69.3 1779.86   158.4 1728.76   178.2 1722.48
   247.4 1678.39   267.2 1671.55   336.5 1630.46   346.4 1626.54   376.1  1620.7
   405.8    1619   415.3    1619   495.3 1620.37   504.8 1624.53   524.5 1638.62
   544.3 1646.46   583.9 1673.73   623.4  1705.1   633.3 1711.02   643.2 1712.87
   722.4 1767.74   732.2 1768.88   742.1 1773.57     752 1784.25   761.9 1811.38
   771.8 1834.29   781.7 1846.95   791.6 1854.23   811.4 1863.82   910.3 1896.03
#Mann= 3 , 0 , 0
       0      .1       0   415.3    .045       0   495.3      .1       0
Bank Sta=415.3,495.3
XS Rating Curve= 0 ,0
Exp/Cntr=0.3,0.1

Type RM Length L Ch R = 1 ,12992.4 ,1006.2,935.9,865.6
XS GIS Cut Line= 2
     1959040.055      189063.309     1959944.864      189923.597
#Sta/Elev= 30
       0 2136.03    49.9  2089.1    79.9 2070.09   129.8  2022.2   169.8 1971.99
   189.8 1950.88   219.7 1927.05   259.7 1886.77   279.7 1858.18   329.6 1802.31
   349.6 1784.76   369.6 1761.21   389.5 1730.43   419.5 1699.94   459.4 1673.74
   499.4 1659.15   529.4 1642.22   589.3 1620.68   619.3 1617.89   678.3  1617.9
   758.3 1623.88     839 1639.51     869 1651.43  1008.8 1688.54  1068.7 1709.16
  1118.7 1734.34  1148.6 1742.82  1168.6  1755.7  1198.6 1820.24  1248.5 1843.74
#Mann= 3 , 0 , 0
       0      .1       0   678.3    .045       0   758.3      .1       0
Bank Sta=678.3,758.3
XS Rating Curve= 0 ,0
Exp/Cntr=0.3,0.1