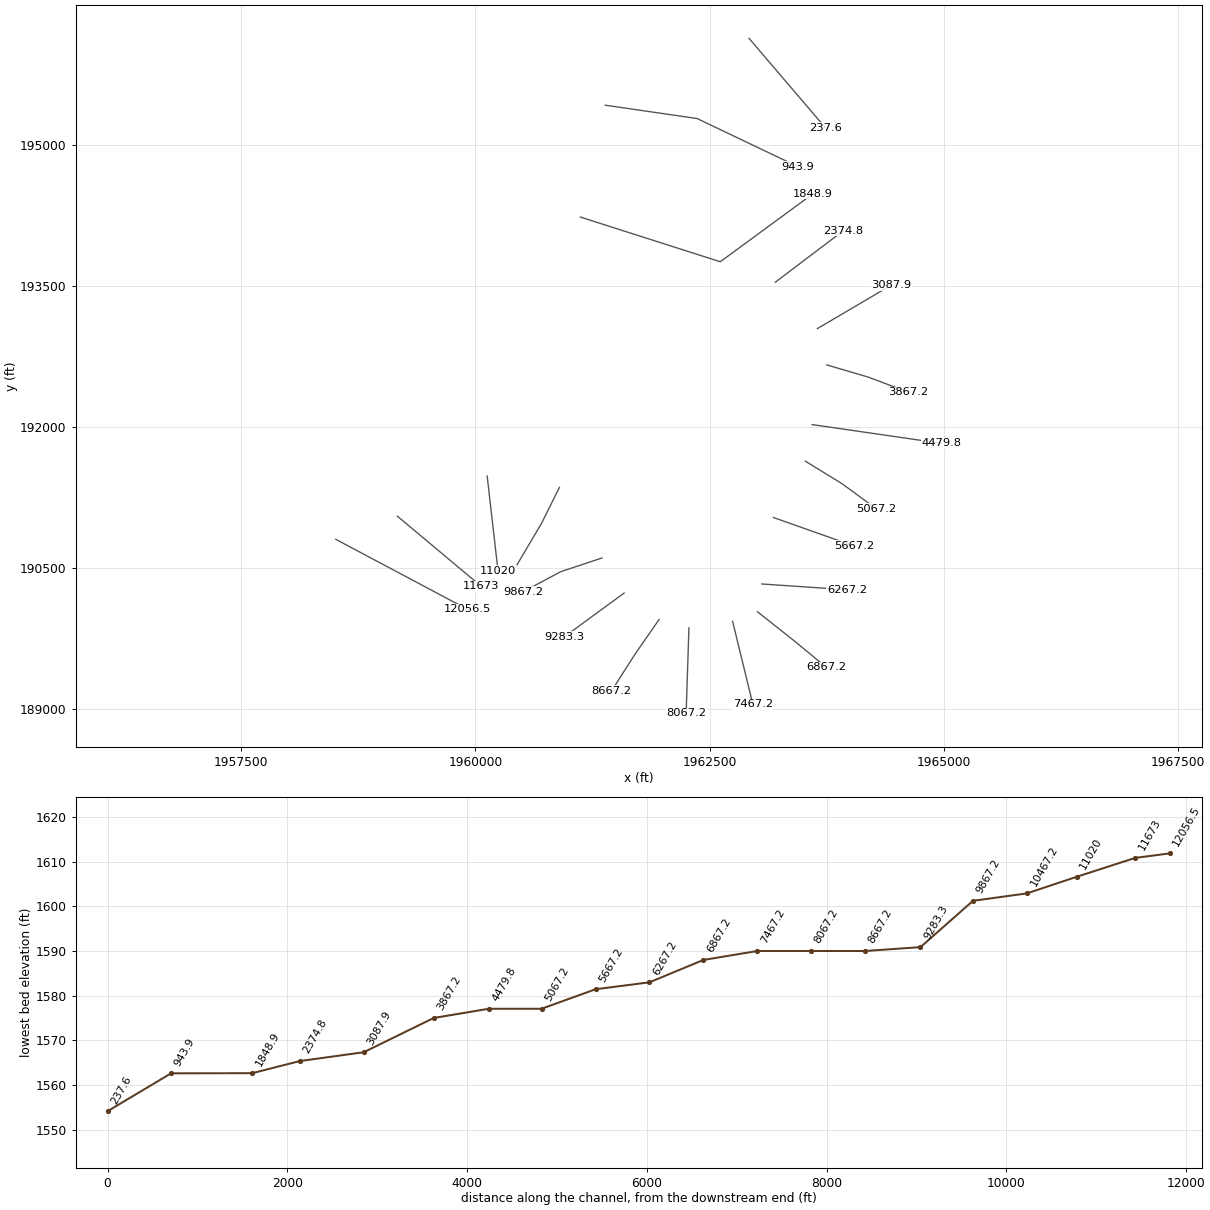
HEC-RAS study BlstnRvr.prj: BlstnRvr

--- BlstnRvr.g01 (geometry) --- (continued)

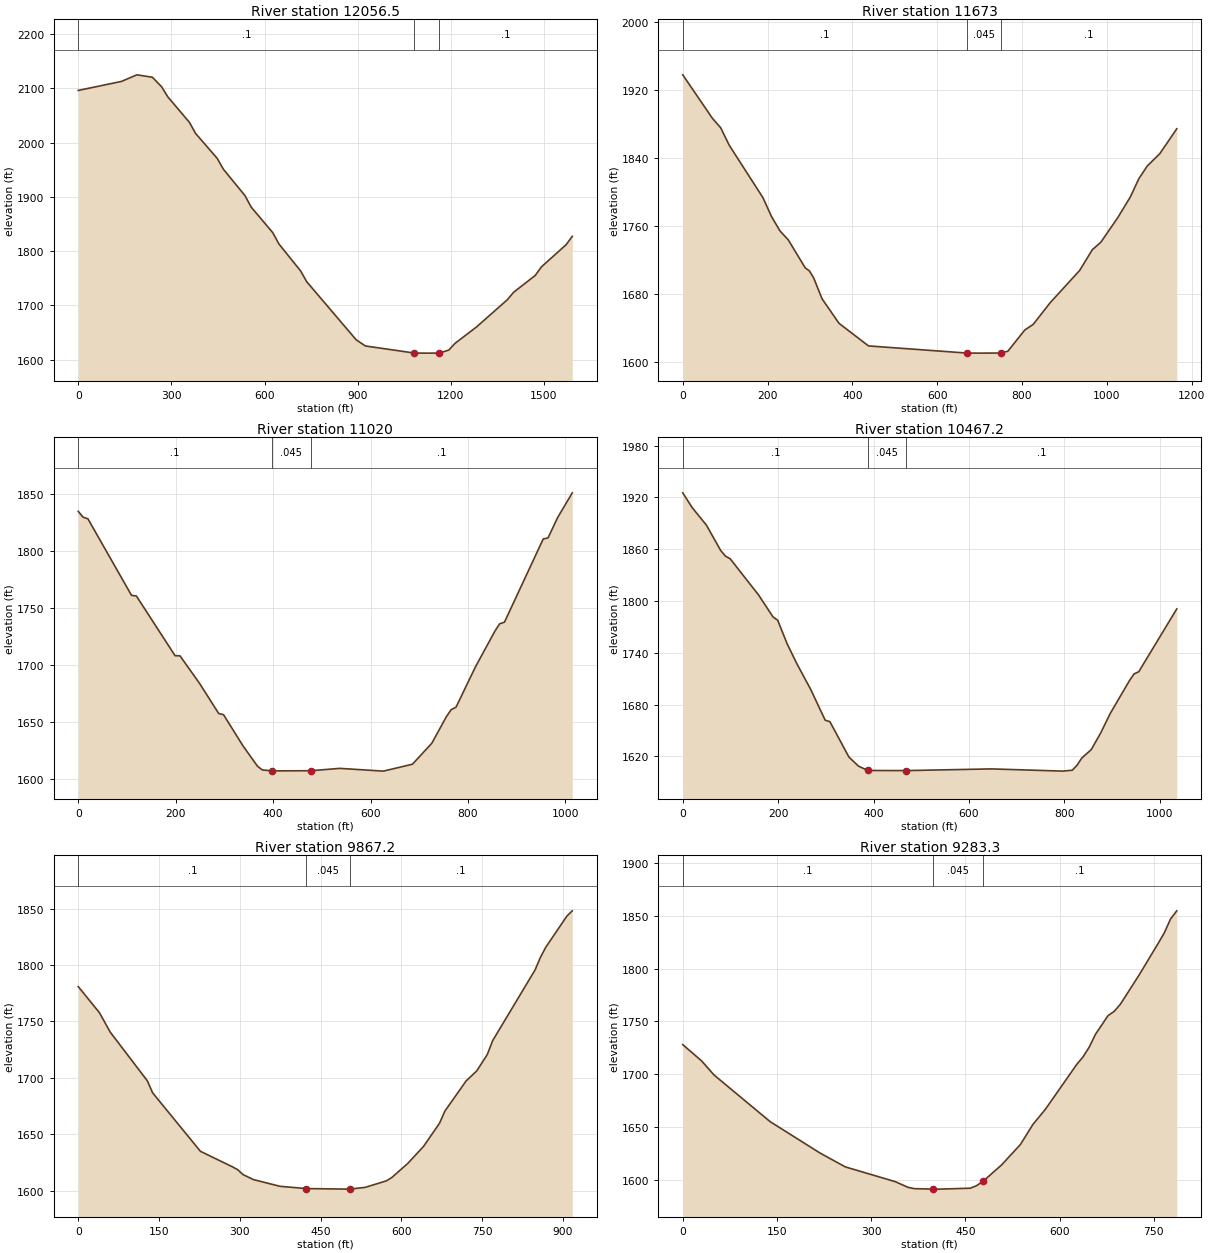
Type RM Length L Ch R = 1 ,12056.5 ,395.2,383.5,371.8
XS GIS Cut Line= 2
     1958510.739      190802.972     1959917.118      190058.179
#Sta/Elev= 30
       0 2096.21   139.2 2112.82     189 2124.99   238.7 2120.58   268.6 2102.95
   288.4  2084.5   358.1 2037.41     378 2016.96   447.6 1970.97   467.5 1950.97
   537.1 1902.25     557 1881.15   626.6 1833.95   646.5 1813.08   716.1 1763.55
     736  1743.5   895.2 1636.44     925 1625.04  1083.1 1611.91  1123.9 1611.82
  1163.1 1611.89  1193.6 1617.41  1213.5 1629.76  1283.1 1660.16  1382.6 1710.46
  1402.4 1724.03  1472.1 1755.09    1492 1770.87  1571.5 1811.72  1591.4 1827.18
#Mann= 3 , 0 , 0
       0      .1       0  1083.1    .045       0  1163.1      .1       0
Bank Sta=1083.1,1163.1
XS Rating Curve= 0 ,0
Exp/Cntr=0.3,0.1

Type RM Length L Ch R = 1 ,11673   ,696,653,610
XS GIS Cut Line= 2
      1959168.17      191049.087     1960062.704      190303.044
#Sta/Elev= 30
       0 1937.82    69.7 1886.89    89.6 1875.54   109.5 1855.17   189.2  1793.4
   209.1 1771.53     229  1754.6   248.9 1743.85   288.7 1711.07   298.7 1707.34
   308.6 1699.33   328.5 1674.64   368.4 1645.86     438 1619.29   669.8  1610.9
   696.9 1610.82   749.8 1610.94   766.6 1613.07   806.4 1637.97   826.3 1644.59
   866.1 1669.95   935.8 1707.97   965.7 1732.34   985.6 1741.02  1025.4 1769.82
  1055.3 1794.31  1075.2 1815.56  1095.1 1830.64    1125 1845.34  1164.8 1874.44
#Mann= 3 , 0 , 0
       0      .1       0   669.8    .045       0   749.8      .1       0
Bank Sta=669.8,749.8
XS Rating Curve= 0 ,0
Exp/Cntr=0.3,0.1

Type RM Length L Ch R = 1 ,11020   ,584.8,552.8,516.7
XS GIS Cut Line= 2
     1960125.659       191477.26     1960241.391      190469.821
#Sta/Elev= 30
       0 1834.65     9.9 1829.55    19.9 1828.13   109.4 1760.89   119.3 1760.39
   198.8 1707.92   208.8 1707.83   248.6 1683.92   288.3 1657.18   298.2 1656.18
     338 1628.89   367.8 1610.97   377.8 1607.64   397.6  1606.8   477.6 1606.92
   536.9    1609   626.3 1606.58     686 1612.65   725.8 1631.08   755.6 1654.32
   765.5 1660.55   775.5 1662.74   815.2    1698     855  1729.3   864.9  1735.9
   874.9 1737.36   954.4 1810.38   964.4 1811.41   984.2 1829.34  1014.1 1850.94
#Mann= 3 , 0 , 0
       0      .1       0   397.6    .045       0   477.6      .1       0
Bank Sta=397.6,477.6
XS Rating Curve= 0 ,0
Exp/Cntr=0.3,0.1

Type RM Length L Ch R = 1 ,10467.2 ,644.4,599.8,568.6
XS GIS Cut Line= 3
     1960897.305       191356.36     1960706.158      190973.371
     1960395.819      190450.793
#Sta/Elev= 30
       0 1925.39    19.9 1908.19    49.8 1887.83    79.6 1858.57    89.6 1852.03
    99.5 1848.96   159.3 1806.79   189.1 1781.71   199.1 1777.73     219  1750.3
   238.9 1727.77   268.8 1697.02   298.6 1661.92   308.6 1660.15   348.4 1619.21
   368.3 1608.76     388 1603.64     468 1603.49   647.2 1605.46   796.7 1602.88
   816.6 1603.92   826.6 1609.62   836.6 1618.04   856.5 1627.82   876.4 1647.25
   896.3 1669.72   936.2 1707.39   946.2 1715.52   956.1 1718.09  1035.8 1790.88
#Mann= 3 , 0 , 0
       0      .1       0     388    .045       0     468      .1       0
Bank Sta=388,468
XS Rating Curve= 0 ,0
Exp/Cntr=0.3,0.1

Type RM Length L Ch R = 1 ,9867.2  ,566.8,584,591.8
XS GIS Cut Line= 3
     1961350.241      190604.297     1960910.203      190458.591
     1960509.775       190245.72
#Sta/Elev= 30
       0 1780.86    39.4 1757.66    59.2 1740.58   128.2 1697.31   138.1  1686.6
   226.8 1634.76     286 1621.05   295.9 1618.48   305.7 1614.14   325.5 1609.63
   374.8  1603.7   423.5  1601.7     503 1601.22   503.5 1601.23   532.5 1602.77
     572 1608.56   581.8 1611.43   611.4 1623.88     641 1639.16   670.6 1659.65
   680.4 1670.32   719.9 1697.15   739.6    1706   759.3 1720.64   769.2 1732.88
     848 1795.65   857.9 1806.79   867.7 1815.63   907.2 1843.51     917 1848.03
#Mann= 3 , 0 , 0
       0      .1       0   423.5    .045       0   503.5      .1       0
Bank Sta=423.5,503.5
XS Rating Curve= 0 ,0
Exp/Cntr=0.3,0.1

Type RM Length L Ch R = 1 ,9283.3  ,597.6,616,636.6
XS GIS Cut Line= 2
     1961587.144      190231.364     1960951.662       189767.94
#Sta/Elev= 30
       0 1727.93    29.9 1712.54    49.8 1699.11   139.4 1654.76     219 1624.94
   258.8 1611.96   338.5 1597.92   358.4 1592.63   368.4 1591.33   398.5 1590.88
   408.2 1590.87     458 1591.75   467.9 1594.17   478.5 1598.53   507.8 1613.93
   537.6 1633.23   557.5 1652.24   577.4 1666.63   627.2 1709.11   637.2 1716.22
   647.1 1725.49   657.1 1737.72     677 1755.36     687  1759.5   696.9 1766.37
   726.8 1794.18   756.6 1823.63   766.6 1833.86   776.6 1847.06   786.5 1854.78
#Mann= 3 , 0 , 0
       0      .1       0   398.5    .045       0   478.5      .1       0
Bank Sta=398.5,478.5
XS Rating Curve= 0 ,0
Exp/Cntr=0.3,0.1

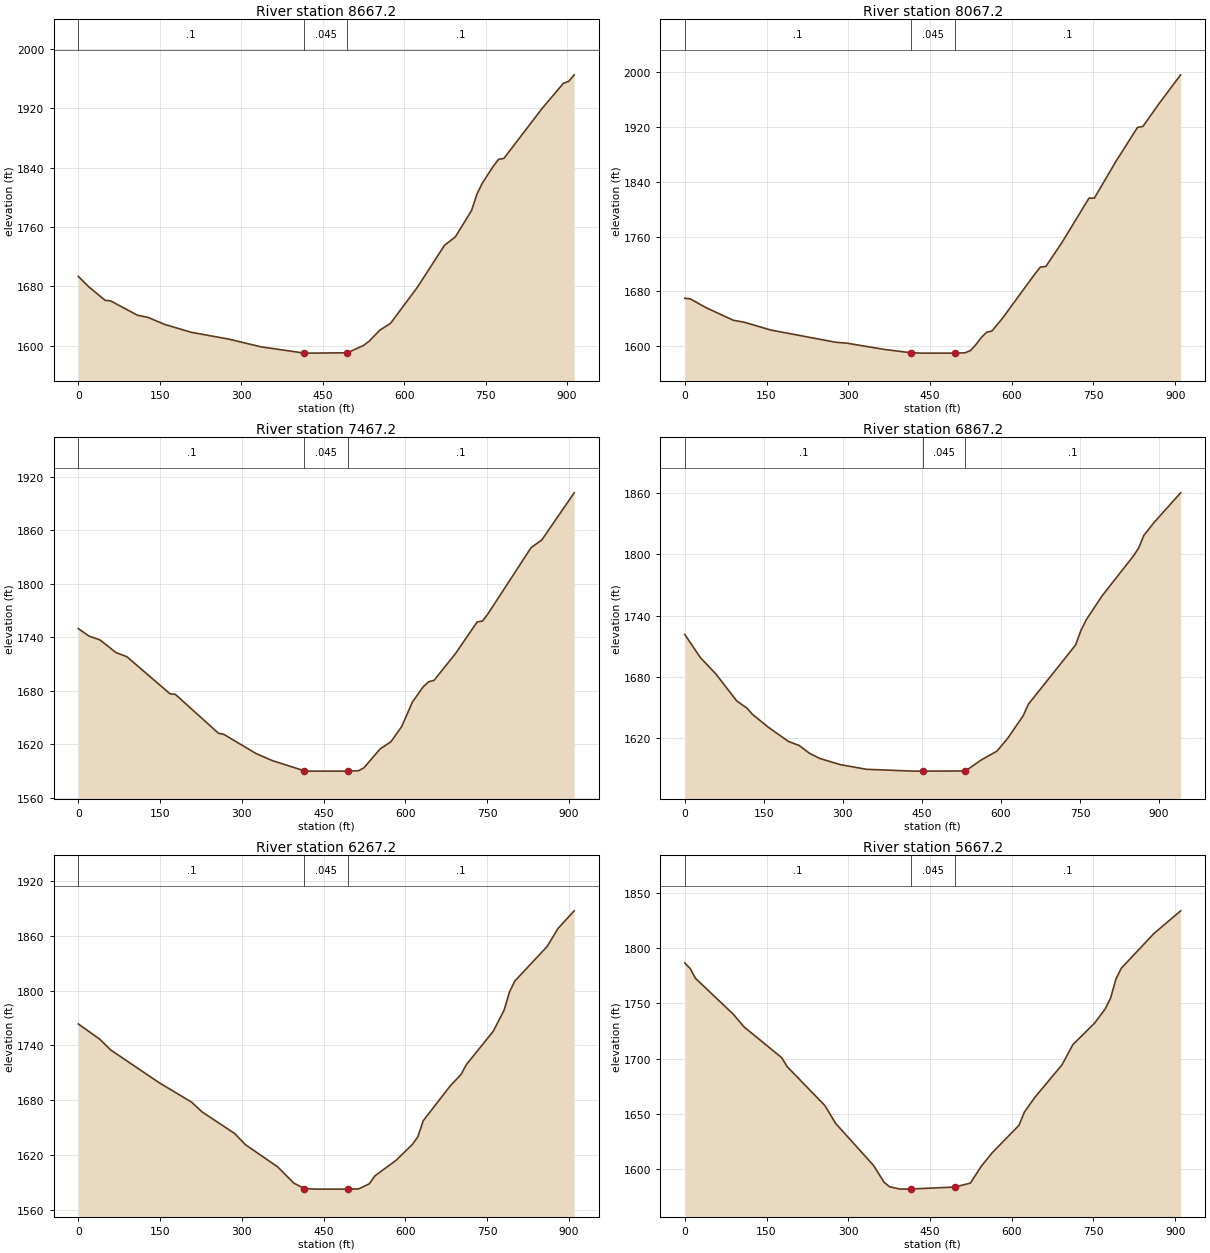
Type RM Length L Ch R = 1 ,8667.2  ,568.1,600,629.8
XS GIS Cut Line= 3
     1961960.707      189950.339      1961700.62      189576.362
      1961453.85       189191.17
#Sta/Elev= 30
       0 1693.45    19.8 1678.93    49.5  1661.1    59.4 1660.44   108.9 1641.09
   128.7 1638.09   158.4  1628.8     208 1618.08   277.3 1608.85   336.7 1598.43
   415.5 1590.09   425.8    1590   495.5 1590.47   525.1 1600.36   535.1 1605.83
     555 1620.86   574.9 1630.13   624.6  1679.1   674.3 1735.36   694.2 1746.63
     724 1782.09     734 1804.26   743.9 1819.05   763.8  1841.6   773.8 1851.12
   783.7 1852.46   853.3 1919.12   893.1 1953.57     903 1956.31     913 1965.05
#Mann= 3 , 0 , 0
       0      .1       0   415.5    .045       0   495.5      .1       0
Bank Sta=415.5,495.5
XS Rating Curve= 0 ,0
Exp/Cntr=0.3,0.1

Type RM Length L Ch R = 1 ,8067.2  ,584.9,600,615.1
XS GIS Cut Line= 3
      1962279.23      189861.078     1962264.293      189406.323
     1962249.356      188951.568
#Sta/Elev= 30
       0 1670.11     9.9  1669.3    39.6 1656.14      89 1638.01   108.8  1635.2
   158.3 1623.63     277 1605.86   296.7 1604.61     366 1595.42     415 1590.55
   435.2    1590     495    1590   514.4 1590.47   524.2 1593.76   534.1 1602.21
     544 1612.56   553.9 1620.49   563.8 1622.34   583.6 1641.51   642.9 1706.02
   652.8 1715.73   662.7  1716.6   692.4 1751.76   741.8 1816.23   751.7  1816.4
   791.3 1869.99   830.9 1919.62   840.8 1921.05   870.4 1954.29     910 1996.35
#Mann= 3 , 0 , 0
       0      .1       0     415    .045       0     495      .1       0
Bank Sta=415,495
XS Rating Curve= 0 ,0
Exp/Cntr=0.3,0.1

Type RM Length L Ch R = 1 ,7467.2  ,562.6,600,635.9
XS GIS Cut Line= 3
     1962745.141      189931.562     1962853.268      189489.596
     1962961.396      189047.631
#Sta/Elev= 30
       0 1749.79    19.8 1741.36    39.6 1737.16    69.2 1722.89      89 1718.34
   168.2 1676.74     178 1676.12   257.2 1632.49   267.1 1631.23   326.4 1609.63
   356.1  1601.8     415  1590.3   425.3    1590     495    1590   514.4 1590.48
   524.2 1593.76   553.9 1614.93   573.7 1622.89   593.5 1640.03   613.3 1667.62
     633 1684.58   642.9 1690.21   652.8 1691.78   692.4 1721.97     732  1757.3
   741.8 1758.32   751.7  1766.3   830.9 1840.55   850.6 1849.19     910 1902.05
#Mann= 3 , 0 , 0
       0      .1       0     415    .045       0     495      .1       0
Bank Sta=415,495
XS Rating Curve= 0 ,0
Exp/Cntr=0.3,0.1

Type RM Length L Ch R = 1 ,6867.2  ,566.5,600,635
XS GIS Cut Line= 3
     1963009.362      190033.463     1963396.159      189728.469
     1963742.608      189444.145
#Sta/Elev= 30
       0 1721.76    29.6 1699.08    59.1 1683.01    98.5 1656.72   118.2 1649.56
   128.1  1643.7   157.6  1631.3     197 1616.92   216.7  1613.2   236.4 1605.52
   256.1  1600.4   295.6 1594.29   344.8 1589.79   433.5    1588   452.6    1588
   532.6 1588.15   562.3 1598.89   592.2 1607.53   612.1 1619.71     642 1642.14
   651.9 1653.44   741.6 1711.53   751.5 1725.47   761.5 1735.86   791.4 1759.27
   851.1 1798.48   861.1 1806.19     871 1818.66     891 1831.66   940.8 1860.33
#Mann= 3 , 0 , 0
       0      .1       0   452.6    .045       0   532.6      .1       0
Bank Sta=452.6,532.6
XS Rating Curve= 0 ,0
Exp/Cntr=0.3,0.1

Type RM Length L Ch R = 1 ,6267.2  ,615,600,585
XS GIS Cut Line= 3
     1963057.301      190328.261     1963511.267      190297.603
     1963965.233      190266.944
#Sta/Elev= 30
       0 1763.54    39.6 1746.74    59.4 1735.09   148.4  1699.3   207.7 1678.15
   227.5 1667.23   286.8 1643.88   306.6 1631.64     366 1607.26   395.6 1589.53
     415 1583.62   435.2    1583     495    1583   514.4 1583.25   534.1 1588.83
     544 1597.34   583.6 1614.72   613.3 1631.99   623.2 1640.28     633 1657.76
   682.5 1695.79   702.3 1708.21   712.2  1719.1   761.6 1755.62   781.4 1778.53
   791.3 1798.49   801.2 1810.52   860.5 1848.28   880.3 1867.83     910 1887.16
#Mann= 3 , 0 , 0
       0      .1       0     415    .045       0     495      .1       0
Bank Sta=415,495
XS Rating Curve= 0 ,0
Exp/Cntr=0.3,0.1

Type RM Length L Ch R = 1 ,5667.2  ,611.7,600,583.8
XS GIS Cut Line= 3
     1963180.614      191035.422     1963609.778      190884.282
     1964038.942      190733.143
#Sta/Elev= 30
       0 1786.84     9.9 1781.77    19.8 1772.74      89 1740.29   108.8 1728.71
     178 1700.73   187.9 1692.66   257.2 1657.26     277 1641.03   346.2 1603.08
     366 1587.56   375.9 1583.59   395.6 1581.45     415 1581.56     495 1583.33
   524.2 1586.94     544 1602.17   563.8 1614.26   613.3  1639.4   623.2 1651.33
   642.9 1665.05   692.4 1694.37   712.2 1712.62   751.7 1731.98   771.5    1745
   781.4 1754.81   791.3 1772.22   801.2 1782.07   860.5 1813.29     910 1834.13
#Mann= 3 , 0 , 0
       0      .1       0     415    .045       0     495      .1       0
Bank Sta=415,495
XS Rating Curve= 0 ,0
Exp/Cntr=0.3,0.1

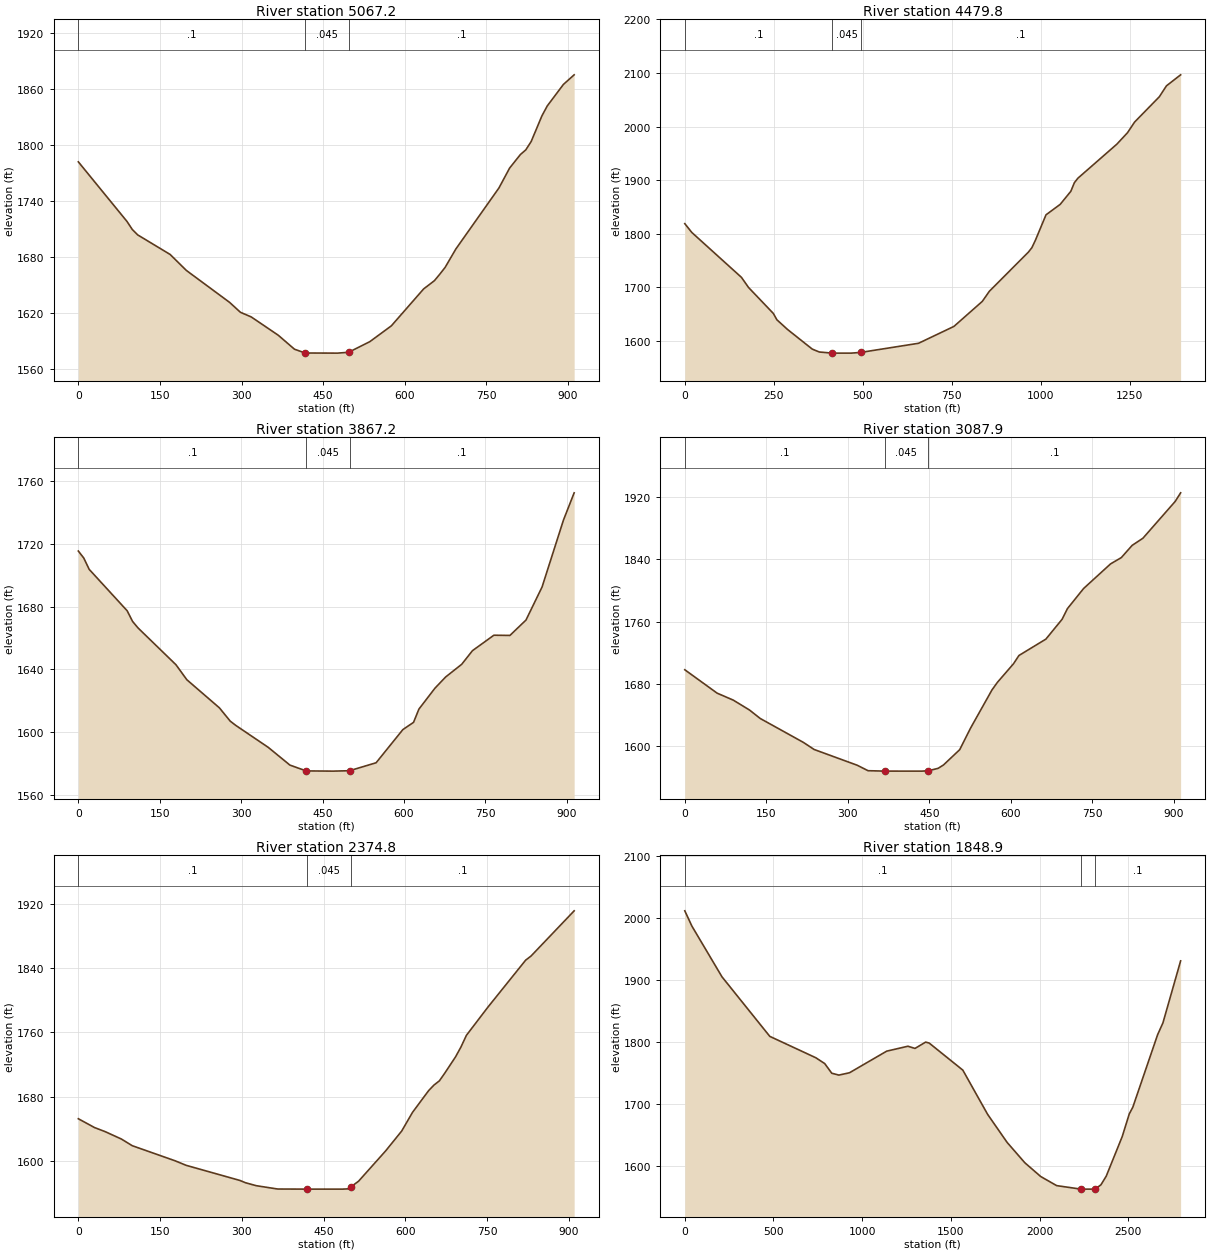
Type RM Length L Ch R = 1 ,5067.2  ,564.7,587.4,614.7
XS GIS Cut Line= 3
     1963521.287       191634.72     1963911.125      191396.484
     1964278.321      191128.357
#Sta/Elev= 30
       0 1781.71    89.4 1717.99    99.3 1709.27   109.2 1703.54   168.8 1682.62
   198.6 1665.54   278.1 1631.38     298 1620.76   317.8 1615.83   367.5 1596.25
   397.3 1581.31   416.9 1577.22   476.6 1577.09   496.9 1577.99   535.9 1589.37
   575.5 1606.31   634.8 1645.77   654.6 1654.59   664.4 1661.46   674.3 1668.81
   694.1 1688.55   773.2 1753.74   792.9 1775.09   812.7 1789.52   822.6 1794.52
   832.5 1803.46   852.2 1830.84   862.1 1841.55   891.8 1864.54   911.5 1874.78
#Mann= 3 , 0 , 0
       0      .1       0   416.9    .045       0   496.9      .1       0
Bank Sta=416.9,496.9
XS Rating Curve= 0 ,0
Exp/Cntr=0.3,0.1

Type RM Length L Ch R = 1 ,4479.8  ,617.5,612.6,602.6
XS GIS Cut Line= 2
     1963594.675      192023.918      1964973.79      191824.519
#Sta/Elev= 30
       0 1818.79    19.9 1802.24   159.2 1718.54   179.2 1699.62   248.8 1651.19
   258.8 1639.36   288.6 1621.34   358.3 1584.57   378.2 1579.16   414.6  1577.1
   467.8 1577.09   494.6 1578.44   656.9 1595.46   756.4 1626.96   836.1 1673.68
     856  1692.6   965.5 1765.54   975.4 1773.89   985.4 1787.83  1015.2 1835.32
    1055 1854.78  1084.9 1879.18  1094.9 1895.22  1104.8 1903.65  1214.3  1967.2
  1244.2 1988.57  1264.1 2008.42  1333.7 2055.71  1353.6 2076.03  1393.5 2096.64
#Mann= 3 , 0 , 0
       0      .1       0   414.6    .045       0   494.6      .1       0
Bank Sta=414.6,494.6
XS Rating Curve= 0 ,0
Exp/Cntr=0.3,0.1

Type RM Length L Ch R = 1 ,3867.2  ,734.2,779.3,828.6
XS GIS Cut Line= 3
     1963751.594      192658.638     1964192.929       192529.13
     1964617.726      192369.247
#Sta/Elev= 30
       0  1715.5      10 1711.06      20 1703.82      90 1677.38     100 1670.58
     110 1666.43     180 1642.91     200 1633.36     260 1615.42     280 1606.92
     290 1604.26     350  1590.2     390 1578.87   419.9 1575.17   469.8 1575.03
   499.9 1575.29   548.8 1580.37   598.1 1601.53   617.8 1606.17   627.7 1614.63
   657.3 1627.98     677 1635.13   706.6 1643.23   726.4 1651.92   765.8 1661.77
   795.4 1661.64     825 1671.44   854.6  1692.5   894.1 1735.28   913.8 1752.66
#Mann= 3 , 0 , 0
       0      .1       0   419.9    .045       0   499.9      .1       0
Bank Sta=419.9,499.9
XS Rating Curve= 0 ,0
Exp/Cntr=0.3,0.1

Type RM Length L Ch R = 1 ,3087.9  ,706.8,713.2,719.5
XS GIS Cut Line= 2
     1963650.222      193045.172     1964437.214      193506.686
#Sta/Elev= 30
       0 1697.89    59.5 1667.76    89.2  1658.8     119 1646.08   138.8 1635.15
   218.2 1604.37     238 1595.23   317.3 1574.93   337.2 1567.91   367.7  1567.4
   436.3 1567.37   447.7 1567.79   466.1 1570.94     476 1575.32   505.8 1594.97
   525.6  1622.5   565.2 1671.92   575.2 1681.67   604.9 1705.69   614.8 1716.25
   664.4 1737.35   694.2 1762.85   704.1 1776.65   733.8 1802.51   783.4  1834.2
   803.2  1842.3   823.1 1858.04   842.9 1867.21   902.4  1914.7   912.3  1925.7
#Mann= 3 , 0 , 0
       0      .1       0   367.7    .045       0   447.7      .1       0
Bank Sta=367.7,447.7
XS Rating Curve= 0 ,0
Exp/Cntr=0.3,0.1

Type RM Length L Ch R = 1 ,2374.8  ,526.6,525.9,525.1
XS GIS Cut Line= 3
      1963202.17      193539.483     1963565.217       193813.75
     1963928.263      194088.017
#Sta/Elev= 30
       0 1652.82    29.7 1641.89    49.5 1636.73    79.1  1627.6    98.9 1619.35
     178  1600.5   197.8 1594.97   296.7 1576.14   306.6 1573.37   326.4 1569.67
     366 1565.51   420.4  1565.4   484.7 1565.39   494.6  1565.7   500.4 1568.23
   514.4 1575.28   563.8 1612.71   593.5 1637.57   613.3 1660.72   642.9 1687.75
   652.8 1694.72   662.7 1699.93   672.6 1709.53   692.4  1729.8   702.3 1742.04
   712.2 1756.41   751.7 1791.46     821 1849.85   830.9 1854.98     910 1911.12
#Mann= 3 , 0 , 0
       0      .1       0   420.4    .045       0   500.4      .1       0
Bank Sta=420.4,500.4
XS Rating Curve= 0 ,0
Exp/Cntr=0.3,0.1

Type RM Length L Ch R = 1 ,1848.9  ,966.4,905,843.6
XS GIS Cut Line= 3
     1961120.234      194231.727     1962613.782      193756.354
     1963604.985      194481.213
#Sta/Elev= 30
       0 2012.17    39.9 1987.58   209.6  1905.6   479.2 1809.41   738.8 1774.86
   788.7 1765.49   828.6 1749.89   868.6 1746.88   928.4 1750.61  1138.1 1785.51
  1257.9 1793.49  1297.8 1789.94  1357.7 1800.14  1377.7 1798.62  1567.4  1754.9
  1707.1 1683.54    1817 1638.19  1916.8 1605.34  2006.6 1583.03  2096.5 1568.34
  2232.9  1562.7  2312.9 1562.69  2346.1 1569.68    2376 1583.68  2465.9 1647.47
  2505.8 1684.18  2525.8 1695.04  2665.6 1812.11  2695.5 1831.16  2795.3  1931.3
#Mann= 3 , 0 , 0
       0      .1       0  2232.9    .045       0  2312.9      .1       0
Bank Sta=2232.9,2312.9
XS Rating Curve= 0 ,0
Exp/Cntr=0.3,0.1

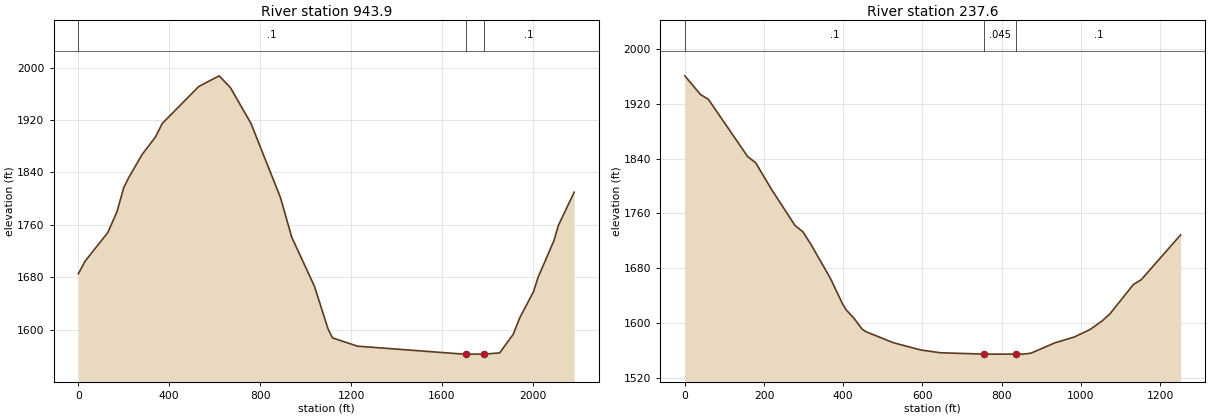
Type RM Length L Ch R = 1 ,943.9   ,729.4,706.3,683.1
XS GIS Cut Line= 3
     1961386.578      195421.845     1962365.979      195280.068
     1963443.156      194767.786
#Sta/Elev= 30
       0 1685.26      30  1704.7     130 1748.35   169.9 1779.91   199.9 1816.78
   219.9 1830.81   279.9 1866.92   339.9 1894.37   369.8 1914.89   529.8 1971.11
   619.8 1987.45   669.7 1969.34   759.7 1914.98   889.6 1801.74   939.6 1740.87
  1039.3 1666.22    1099 1601.27  1118.8 1587.44  1228.2 1574.82  1695.3 1562.65
  1706.2 1562.68  1786.2  1562.7  1854.4 1564.51    1914 1592.85  1943.8  1618.6
  2003.5 1657.97  2023.4 1679.66  2092.9 1735.42  2112.8 1758.88  2182.4  1809.8
#Mann= 3 , 0 , 0
       0      .1       0  1706.2    .045       0  1786.2      .1       0
Bank Sta=1706.2,1786.2
XS Rating Curve= 0 ,0
Exp/Cntr=0.3,0.1

Type RM Length L Ch R = 1 ,237.6   ,237.1,237.6,238.2
XS GIS Cut Line= 2
     1962920.583      196133.219     1963734.924      195182.275
#Sta/Elev= 30
       0 1960.88    39.8 1933.52    59.6 1926.52     159 1842.69   178.8 1834.06
   218.6 1795.29   278.2 1742.23   298.1    1733     318 1715.03   367.6 1664.99
   397.4 1628.73   407.4 1618.89   427.3 1606.57   447.1 1591.08   457.1 1587.03
   526.6 1570.86   596.2  1560.2   645.9 1556.15     756  1554.2     836  1554.2
   854.5 1554.18   874.4 1555.59     934 1570.57   983.7 1579.24  1023.4 1590.19
  1053.2 1602.44  1073.1 1612.77  1132.7 1655.93  1152.6 1662.95    1252 1728.47
#Mann= 3 , 0 , 0
       0      .1       0     756    .045       0     836      .1       0
Bank Sta=756,836
XS Rating Curve= 0 ,0
Exp/Cntr=0.3,0.1

Chan Stop Cuts=-1
Use User Specified Reach Order=0
Composite Channel Slope=5